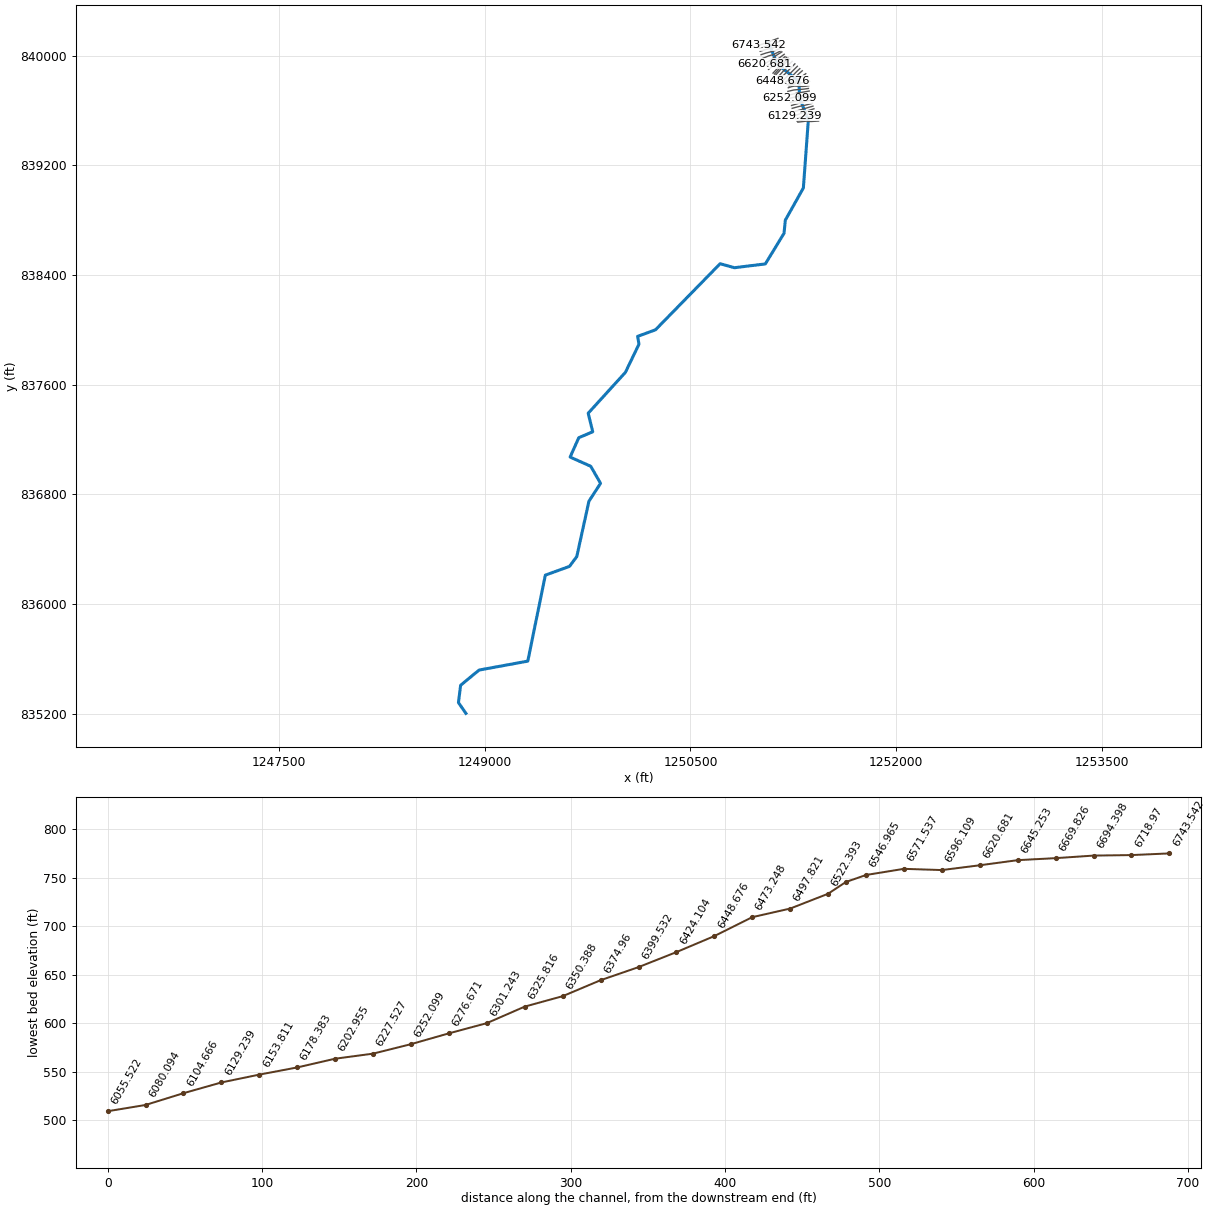
--- 77_ras.prj (project) ---

Proj Title=77
Current Plan=p01
Default Exp/Contr=0.3,0.1
English Units
Geom File=g01
Flow File=f01
Plan File=p01
Y Axis Title=Elevation
X Axis Title(PF)=Main Channel Distance
X Axis Title(XS)=Station
BEGIN DESCRIPTION:
RFD model 77 exported to HEC-RAS
END DESCRIPTION:

--- 77_ras.p01 (plan) ---

Plan Title=Plan 01
Program Version=4.10
Short Identifier=Plan 01
Geom File=g01
Flow File=f01
Subcritical Flow
Calc Critical at every XS
Secant Critical Depth

--- 77_ras.f01 (steady flow) ---

Flow Title=Flow 01
Program Version=5.01
Number of Profiles= 5
Profile Names=10yr,25yr,50yr,100yr,500yr
River Rch & RM=77,103,6743.542
    99.3  175.76  248.87  335.69  587.39
River Rch & RM=77,103,6055.522
   111.8  198.41  281.64  380.92  671.34
River Rch & RM=77,103,5932.661
  115.54   205.2  291.48  394.52   696.7
River Rch & RM=77,103,5834.373
  119.28  211.98  301.32  408.14  722.15
River Rch & RM=77,103,5711.506
  152.79  273.01  390.09  531.35   954.4
River Rch & RM=77,103,5613.205
  157.12  280.92  401.62   547.4   984.9
River Rch & RM=77,103,5514.904
  162.67  291.07  416.45  568.05 1024.22
River Rch & RM=77,103,5416.603
  165.76  296.72  424.69  579.54 1046.13
River Rch & RM=77,103,5318.302
  171.93     308  441.17  602.54 1090.05
River Rch & RM=77,103, 5170.85
  174.39  312.51  447.77  611.74 1107.67
River Rch & RM=77,103,5072.549
  251.55  454.43  656.14  903.89 1673.48
River Rch & RM=77,103,4930.414
  270.42  489.29  707.55  976.31 1815.51
River Rch & RM=77,103,4777.646
  288.04  521.89  755.69 1044.22 1949.25
River Rch & RM=77,103,4630.195
  290.47  526.38  762.33  1053.6 1967.77
River Rch & RM=77,103,4531.894
  477.06  873.99 1279.01 1787.67 3440.93
River Rch & RM=77,103,4384.442
  483.64   886.3  1297.4 1813.94  3494.4
River Rch & RM=77,103,4286.141
  490.81  899.73 1317.47 1842.61  3552.8
River Rch & RM=77,103, 4187.84
  494.99  907.57 1329.18 1859.34 3586.91
River Rch & RM=77,103,4089.539
  503.95  924.35 1354.27 1895.21 3660.09
River Rch & RM=77,103,3942.088
  511.11  937.78 1374.35 1923.93 3718.73
River Rch & RM=77,103,3843.787
  524.83  963.51 1412.84    1979 3831.34
River Rch & RM=77,103,3658.416
  536.75  985.88 1446.33 2026.93 3929.49
River Rch & RM=77,103, 3519.59
  545.09 1001.53 1469.77 2060.51 3998.33
River Rch & RM=77,103,3377.232
  549.85 1010.48 1483.17  2079.7 4037.71
River Rch & RM=77,103,3249.757
  676.86 1249.57 1842.13 2595.22 5102.59
River Rch & RM=77,103,3113.537
  679.82 1255.16 1850.53 2607.31 5127.72
River Rch & RM=77,103,2979.697
     681 1257.39 1853.89 2612.15 5137.77
River Rch & RM=77,103,2841.098
  682.78 1260.74 1858.93 2619.41 5152.86
River Rch & RM=77,103,2637.218
  692.24  1278.6 1885.81 2658.11 5233.37
River Rch & RM=77,103, 2462.43
  699.93 1293.11 1907.65 2689.57 5298.87
River Rch & RM=77,103,2345.088
  706.43 1305.38 1926.14  2716.2 5354.34
River Rch & RM=77,103, 2048.27
  794.33  1471.6 2176.75 3077.77 6110.47
River Rch & RM=77,103,1836.384
  796.69 1476.06 2183.48  3087.5 6130.88
River Rch & RM=77,103,1664.038
  813.17 1507.28 2230.62 3155.62 6273.95
River Rch & RM=77,103, 1365.05
  820.82 1521.77 2252.51 3187.26 6340.47
River Rch & RM=77,103,1178.186
  913.05 1696.72 2517.09 3570.24 7148.41
River Rch & RM=77,103,986.6639
  945.88 1759.08 2611.55 3707.18 7438.55
River Rch & RM=77,103,300.2457
  971.07 1806.96 2684.11 3812.45    7662
River Rch & RM=77,103,       0
  975.75 1815.87 2697.61 3832.05 7703.64
Boundary for River Rch & Prof#=77,103,1
Up Type= 0
Dn Type= 2
Boundary for River Rch & Prof#=77,103,2
Up Type= 0
Dn Type= 2
Boundary for River Rch & Prof#=77,103,2
Up Type= 0
Dn Type= 2
Boundary for River Rch & Prof#=77,103,2
Up Type= 0
Dn Type= 2
Boundary for River Rch & Prof#=77,103,2
Up Type= 0
Dn Type= 2

--- 77_ras.g01 (geometry) ---

Geom Title=77
Program Version=4.10

River Reach=77,103
Reach XY= 30
1251066.38943052 840099.131163851251133.05607286839937.464543015
1251290.89264166839811.1745969951251295.55601797839692.464610636
1251359.12180829839526.5391803231251323.05599052839034.131471023
1251191.38935566838799.1315443521251182.22268888838704.131572664
1251045.95340553838480.5235553381250820.60618329838452.745777547
1250716.09229442838481.9124442191250244.72294354 837999.96514155
1250114.26937777837952.1381386671250124.72297576837895.798509181
 1250025.5563322 837689.965239571249754.13482913837391.721471995
1249787.22305614837256.6320412761249685.55641803837213.298723698
1249622.38261601837072.117153913  1249772.795259837005.036726594
1249844.18817154836880.4678483311249759.55275488836750.259515002
1249671.01108822836346.6136816741249617.62567157836274.999098331
1249441.84442157836211.1970150171249313.72973654835584.290916458
1248958.76464328835519.1201838251248824.10897473 835408.51017724
1248808.07853469 835281.869730831248862.58201593835203.320591271

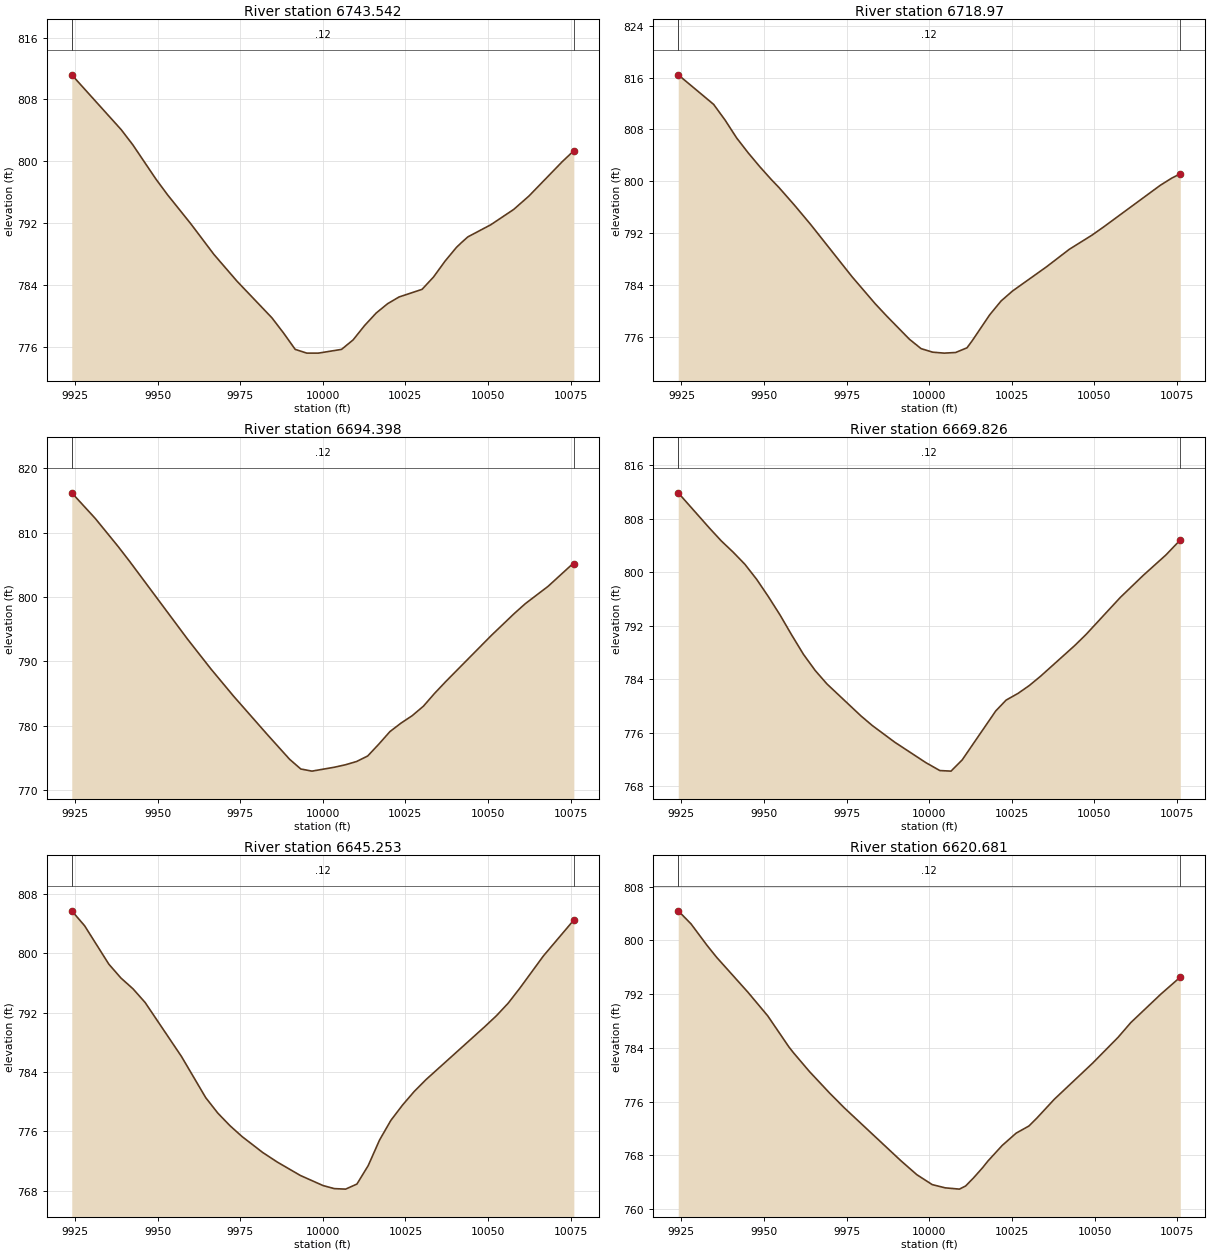
Type RM Length L Ch R = 1 ,6743.542,24.572100,24.572100,24.572100
XS GIS Cut Line= 5
1251137.74671553840125.304702614 1251067.6806198840098.554249451
1251065.81251611840097.8399745721251052.50534223840092.872376632
 1250994.9723619840073.229170882
#Sta/Elev= 30
9924.001811.17969938.963804.08669942.475802.12989949.498 797.681 9953.01795.6536
9960.034791.91069967.058787.93269974.081 784.4549984.617779.73169988.128777.7696
 9991.64775.65929995.152 775.1759998.664775.173810005.67775.656910009.18776.8866
10012.68778.758810016.17780.366110019.64781.5737 10023.1782.443110030.04783.4227
 10033.5785.010110036.97787.053710040.44788.846810042.07789.509410043.91790.2129
10050.84791.777910057.77793.756910062.38795.486210072.53799.9606   10076801.3595
#Mann= 3 , 0 , 0
9924.001    0.12       09924.001    0.12       0   10076    0.12       0
#XS Ineff= 2 , 0
       0                               0
Bank Sta=9924.001,10076
Exp/Cntr=0.3,0.1

Type RM Length L Ch R = 1 , 6718.97,24.572200,24.572200,24.572200
XS GIS Cut Line= 5
 1251146.9639303840101.1287012091251076.45625102840075.602596628
1251074.58814733840074.8883217481251069.43694931840073.030192238
1251003.15463257840052.055462906
#Sta/Elev= 30
9924.014816.44649934.725811.88339938.215809.44079941.704806.68779945.193804.3922
9948.682802.26619952.171800.2786 9954.49799.0462 9959.15796.33949964.128793.3079
9976.596785.27529983.574781.11949987.064 779.2119994.042775.57479997.531 774.147
10001.03773.599310004.52773.451310007.99773.548410011.43774.273610012.98775.3494
10018.31779.377510021.75781.510710025.19783.040210035.52786.7956 10042.4789.4915
10049.28791.684410052.72792.921810069.93799.376410073.37800.4764   10076801.1631
#Mann= 3 , 0 , 0
9924.014    0.12       09924.014    0.12       0   10076    0.12       0
#XS Ineff= 2 , 0
       0                               0
Bank Sta=9924.014,10076
Exp/Cntr=0.3,0.1

Type RM Length L Ch R = 1 ,6694.398,24.572100,24.572100,24.572100
XS GIS Cut Line= 6
1251153.41270962840074.6826109651251109.03482871840058.334585482
1251082.19706111 840051.595959551251080.23814702840051.192653766
1251050.62171015840044.1486927781251008.03079104840031.099096462
#Sta/Elev= 28
9924.036816.16989931.153812.18569938.145807.78069941.642805.45419959.124793.4023
9966.116788.82549973.051784.54829983.199778.62319989.965774.76559993.347773.2565
 9996.73772.924610003.47773.525410006.84 773.90910010.21 774.41410013.59775.2721
10016.96777.114810020.33779.0676 10023.7780.392410027.07781.540210030.45783.0101
10033.86785.017710037.29786.875710051.02794.007510057.88797.376410061.31798.9501
10068.17801.628810075.04804.852710075.99805.1848
#Mann= 3 , 0 , 0
9924.036    0.12       09924.036    0.12       010075.99    0.12       0
#XS Ineff= 2 , 0
       0                               0
Bank Sta=9924.036,10075.99
Exp/Cntr=0.3,0.1

Type RM Length L Ch R = 1 ,6669.826,24.572200,24.572200,24.572200
XS GIS Cut Line= 6
1251158.82161123840053.415057234 1251115.0525476840035.333167596
 1251088.4548939840027.9486031741251086.53924132840027.373907458
1251051.24955896840018.3513739371251014.68209859840006.108040121
#Sta/Elev= 30
9924.039811.86839933.567806.55639937.117 804.6629940.667803.00119944.217801.1904
9947.766798.94869951.316 796.3649954.866793.60429958.416790.59629961.965787.7171
9965.515785.31119969.065783.30569979.375778.5225 9982.78777.0969 9989.59774.6017
    9999771.552310003.21770.3728 10006.6770.288510009.98771.968210020.14779.2844
10023.27780.899910026.91781.9117 10030.3783.081610033.69784.463710043.98789.0259
10047.44790.696210057.82796.234410064.74799.522510071.66802.597210075.99804.8309
#Mann= 3 , 0 , 0
9924.039    0.12       09924.039    0.12       010075.99    0.12       0
#XS Ineff= 2 , 0
       0                               0
Bank Sta=9924.039,10075.99
Exp/Cntr=0.3,0.1

Type RM Length L Ch R = 1 ,6645.253,24.572100,24.572100,24.572100
XS GIS Cut Line= 6
1251160.04804833840034.6703903421251108.31749789 840008.90377755
1251092.03774338840003.5018092211251090.05528757840003.237481838
1251070.71812792839997.4579719871251020.12157842839976.460056913
#Sta/Elev= 30
9924.055805.72489927.933 803.7179935.263798.54459938.928796.66989942.594795.2094
9946.259793.36589957.255786.08989964.585780.54569968.251778.46099971.916776.7709
9975.581775.30389981.847  773.159986.308771.84749993.222770.060210000.09768.6993
10003.48768.2894 10006.9768.220210010.33768.902310013.75771.394610017.18  774.84
 10020.6777.485410024.13779.550510027.68781.387110031.24782.9824   10049790.1093
10052.55791.5915 10056.1793.280810059.65795.319110066.76799.650910075.96804.4892
#Mann= 3 , 0 , 0
9924.055    0.12       09924.055    0.12       010075.96    0.12       0
#XS Ineff= 2 , 0
       0                               0
Bank Sta=9924.055,10075.96
Exp/Cntr=0.3,0.1

Type RM Length L Ch R = 1 ,6620.681,24.572100,24.572100,24.572100
XS GIS Cut Line= 6
1251166.42672893840026.4601990731251120.46646732839997.759894201
1251104.99836188 839983.91770013  1251103.703065 839982.39382153
1251084.78713344839966.3318440261251042.13189102839940.029610032
#Sta/Elev= 30
9924.057804.41669927.934802.46559932.749799.2807 9935.67797.49119945.137 792.288
9951.141788.75569957.525784.13949958.877783.28829963.719780.48359969.913777.2237
9974.349775.02929991.422767.16729996.226765.096210000.88763.6161 10004.8763.1347
10009.11762.942310010.99763.410910013.41764.630710016.06766.098710017.72767.1202
10022.02769.433110026.27771.284710030.13772.346610032.54773.529110037.83776.3428
 10049.4781.713510057.11785.567110060.96787.761910070.05792.005510075.93 794.543
#Mann= 3 , 0 , 0
9924.057    0.12       09924.057    0.12       010075.93    0.12       0
#XS Ineff= 2 , 0
       0                               0
Bank Sta=9924.057,10075.93
Exp/Cntr=0.3,0.1

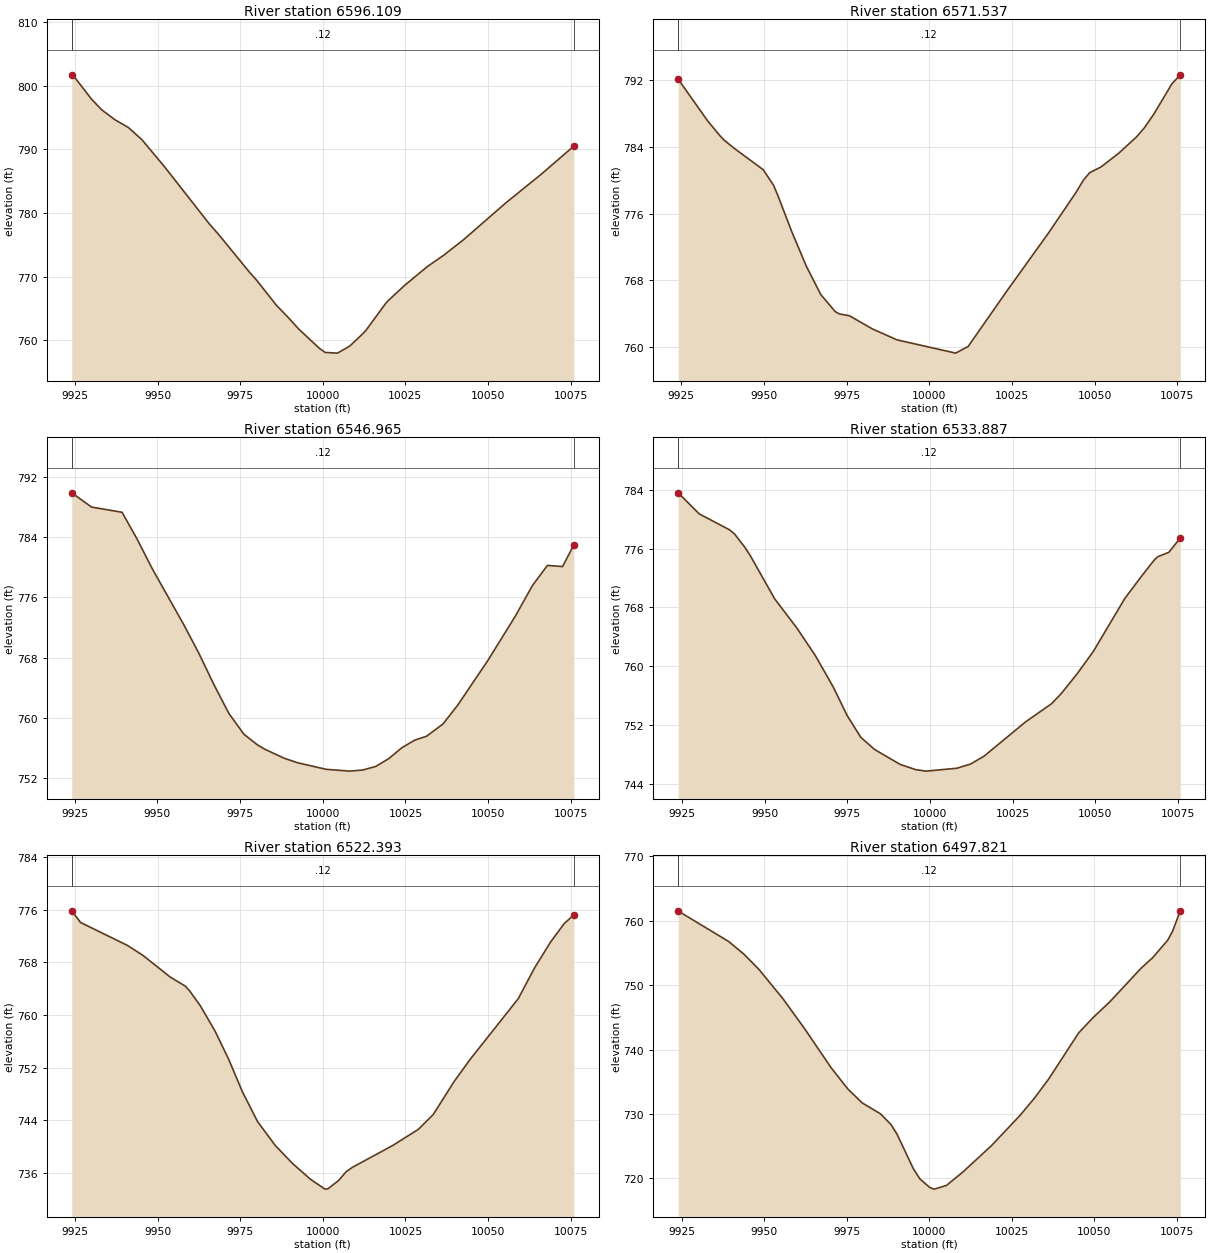
Type RM Length L Ch R = 1 ,6596.109,24.572200,24.572200,24.572200
XS GIS Cut Line= 6
1251183.51915729840008.9816930471251136.91662511839974.695222849
1251122.05463042839966.2009032511251120.23078739839965.380173949
1251109.96498604 839959.707930111251057.40775221839924.502206309
#Sta/Elev= 30
9924.025801.69739924.889801.30949929.981797.89599933.035 796.2289937.108794.6402
9941.181793.41669945.254791.51429952.126 787.247 9965.62778.31729968.734776.4752
9977.839 770.6899979.807769.55859986.015765.48549989.468763.63929992.627761.8313
    9999758.741410000.72758.107210004.45757.9996 10008.2759.124110011.95760.9722
10013.06761.570810018.96765.757410019.81766.249210024.86768.677110031.65771.5889
10036.65773.390510042.54775.778510055.35781.567410066.12786.089110075.99790.5087
#Mann= 3 , 0 , 0
9924.025    0.12       09924.025    0.12       010075.99    0.12       0
#XS Ineff= 2 , 0
       0 9988.05        10025.33       0
Bank Sta=9924.025,10075.99
Exp/Cntr=0.3,0.1

Type RM Length L Ch R = 1 ,6571.537,24.572100,24.572100,24.572100
XS GIS Cut Line= 6
1251189.07026475839991.6083675991251139.23414043839948.074106383
1251131.69534913839943.5589352391251129.83839573839942.816153939
1251115.24613916839934.5071316751251069.24955644839898.913493028
#Sta/Elev= 30
9924.039792.09679932.918787.1151 9936.69785.31299937.905784.80589941.046 783.795
9949.759781.25149952.865 779.3989954.115 778.2289958.472773.74249962.839769.6505
9967.184766.27749971.541764.23969972.813763.96969975.897763.73649982.787 762.165
9990.213760.859610007.98759.265910011.76760.066610023.61766.790410036.05773.6531
10044.35778.503710046.61779.9835 10048.5780.887110051.97781.585410057.33783.2316
10062.69785.180110065.09786.280210068.05787.984310073.39791.540510075.95792.6245
#Mann= 3 , 0 , 0
9924.039    0.12       09924.039    0.12       010075.95    0.12       0
#XS Ineff= 2 , 0
       09985.216        10011.82       0
Bank Sta=9924.039,10075.95
Exp/Cntr=0.3,0.1

Type RM Length L Ch R = 1 ,6546.965,13.077900,13.077900,13.077900
XS GIS Cut Line= 6
1251200.20664019839986.5526989351251164.80612817839951.535252997
1251150.22924753 839931.058436091251149.18634746839929.351872452
  1251132.323359 839904.072263791251101.73573269839871.696408405
#Sta/Elev= 30
9924.071789.84599930.062 787.9569939.292787.26439943.848783.69759948.521779.6901
9957.844772.44119962.366768.68929967.175764.31669971.595760.58349976.144757.8231
9980.171756.43339982.397755.84689988.226754.65859992.253754.0552   10001753.1704
10008.12752.929110012.06753.0737   10016753.549610019.95 754.58610023.89756.0292
10027.84757.043910031.39 757.56110036.35 759.18410040.86761.716710049.89767.5853
10058.18773.446510063.43 777.56310067.94780.218310072.51780.065310075.93782.9299
#Mann= 3 , 0 , 0
9924.071    0.12       09924.071    0.12       010075.93    0.12       0
#XS Ineff= 2 , 0
       09989.627        10018.84       0
Bank Sta=9924.071,10075.93
Exp/Cntr=0.3,0.1

Type RM Length L Ch R = 1 ,6533.887,11.494300,11.494300,11.494300
XS GIS Cut Line= 6
1251211.09289652839980.4868977131251182.20182065839950.716507966
1251161.62884198839924.3000678661251160.34847314839922.763625343
1251138.30841547839893.2558982891251112.58381883839865.094289495
#Sta/Elev= 30
9923.843783.6275  9930.2780.75779939.343778.58939940.879778.02659943.915 776.255
 9945.59775.10869953.059769.15999959.723765.21399965.327761.45049970.802757.1213
9974.994753.24219979.118750.28619983.277748.63949991.013746.60659995.752745.8908
 9998.81745.693610008.17746.088710012.26746.645710016.36747.724210029.04752.4353
10036.83754.887810039.74756.2581 10044.6758.986610049.47762.015510058.98769.2301
10064.06772.267410067.87774.458710068.93 774.91610072.31775.519610075.78 777.475
#Mann= 3 , 0 , 0
9923.843    0.12       09923.843    0.12       010075.78    0.12       0
#XS Ineff= 2 , 0
       09988.153        10019.61       0
Bank Sta=9923.843,10075.78
Exp/Cntr=0.3,0.1

Type RM Length L Ch R = 1 ,6522.393,24.572100,24.572100,24.572100
XS GIS Cut Line= 6
1251220.76716443839974.3305454051251191.87608857839944.560155658
 1251171.3031099839918.1437155571251170.02274105839916.607273035
1251147.98268338839887.0995459811251122.25808674839858.937937186
#Sta/Elev= 30
9924.033775.82149926.695774.05349940.828770.58589945.539769.07069953.814765.7737
9958.385764.39369959.672763.69079962.957761.39599967.347757.61339971.506753.3106
9975.664748.3695 9980.25743.8401 9985.59740.22389990.929737.43599996.269735.0815
10000.66733.582110001.54 733.62810004.77734.885410007.02736.207810008.86736.8627
10021.15 740.20410028.95742.666210033.43744.910610039.68749.870210044.55753.2516
10059.14762.4871   10064767.084610068.87771.045310073.05773.883710075.97 775.202
#Mann= 3 , 0 , 0
9924.033    0.12       09924.033    0.12       010075.97    0.12       0
#XS Ineff= 2 , 0
       09986.847        10020.25       0
Bank Sta=9924.033,10075.97
Exp/Cntr=0.3,0.1

Type RM Length L Ch R = 1 ,6497.821,24.572100,24.572100,24.572100
XS GIS Cut Line= 6
1251241.17653877839957.2549773491251214.44216431 839930.04063947
1251190.14406988839902.3490457511251188.84248709839900.830532583
1251162.39765229839870.1224602851251138.55008569839845.239819754
#Sta/Elev= 30
 9924.01761.50489939.231756.7934 9943.83 754.8449948.429752.4525 9955.78747.8391
 9962.16743.31349970.304737.16279975.317733.88839979.682731.71339985.227730.0127
9988.411728.35029990.201726.88419995.176721.49729997.141719.912810000.17718.5674
10001.48718.3152 10005.2718.888510010.22720.9962 10018.8725.057210027.46729.7631
10031.79732.417210036.12735.3982 10045.2742.568910049.48 744.90610054.68747.4239
10064.16752.650210067.66 754.27910072.21757.004110073.65758.378410075.99761.5414
#Mann= 3 , 0 , 0
 9924.01    0.12       0 9924.01    0.12       010075.99    0.12       0
#XS Ineff= 2 , 0
       0                               0
Bank Sta=9924.01,10075.99
Exp/Cntr=0.3,0.1

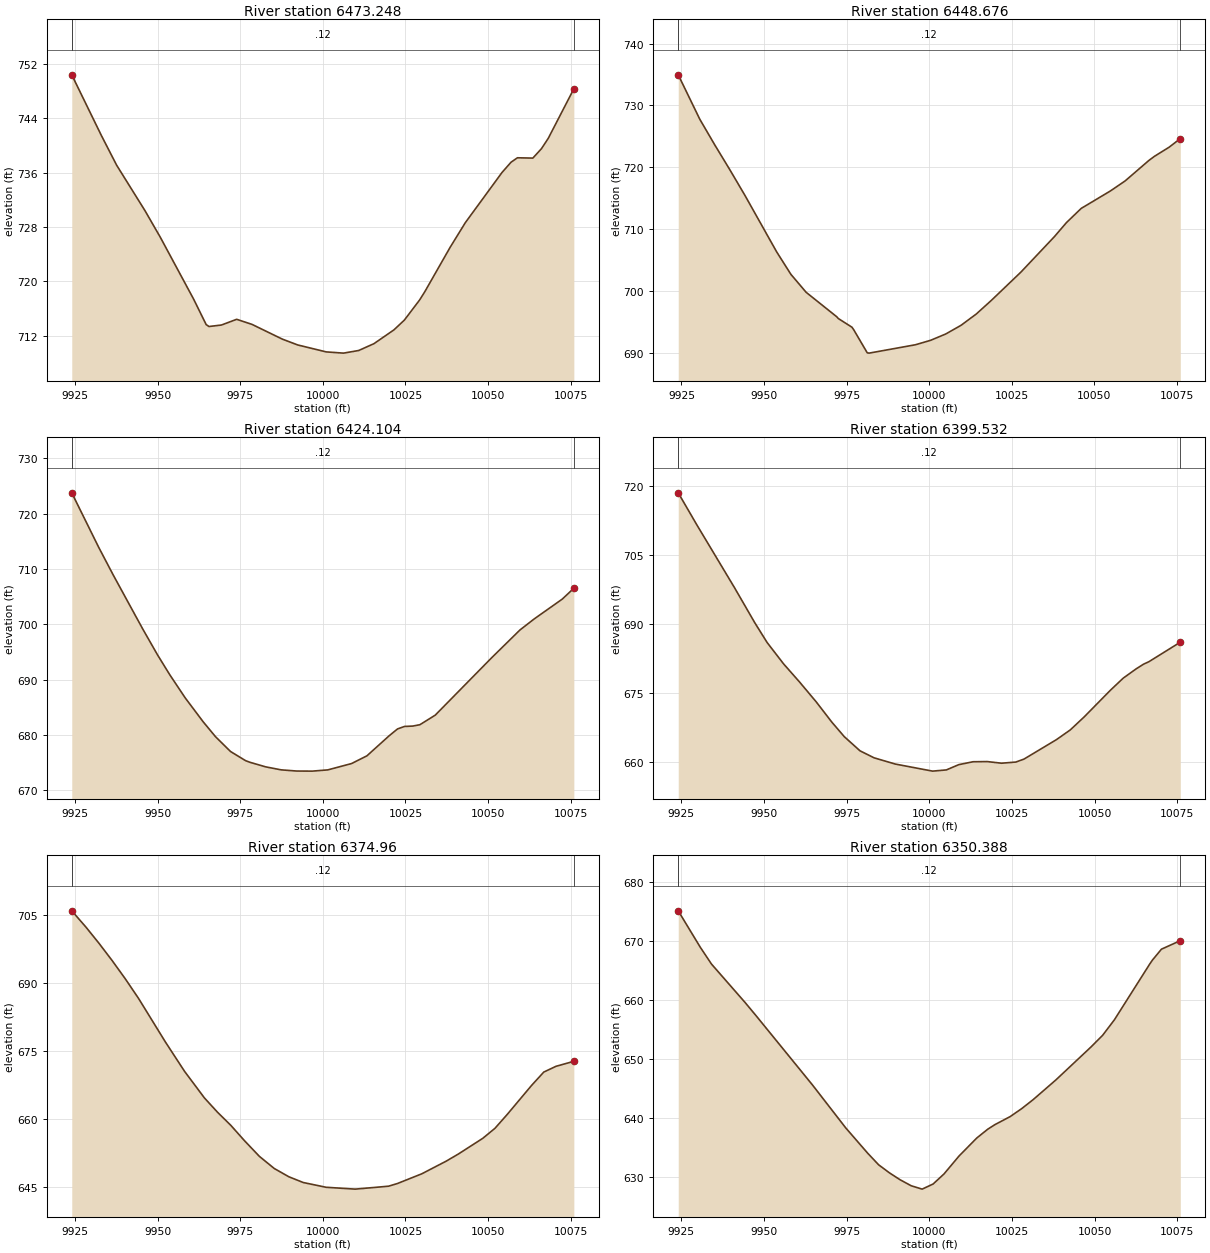
Type RM Length L Ch R = 1 ,6473.248,24.572200,24.572200,24.572200
XS GIS Cut Line= 4
1251261.26804297839939.2152541261251208.50707581839885.927743386
1251207.09286221839884.5135298631251154.41418668839831.150418135
#Sta/Elev= 30
9924.011750.37369932.917741.5057 9937.58737.09499946.223730.3572 9950.84726.4634
9960.895717.38929964.691713.64869965.558713.36199969.308713.58079973.924714.4224
9978.541  713.689987.775711.50249992.392 710.653   10001709.631210006.25709.4486
10010.86709.835210015.47710.836810021.54 712.87410024.69714.3106 10029.3717.2659
10030.88718.488810038.52724.995210043.13728.631610054.23736.007610056.96737.5165
 10058.9738.173210063.57738.128210066.18739.514210068.24 741.03710075.98748.3131
#Mann= 3 , 0 , 0
9924.011    0.12       09924.011    0.12       010075.98    0.12       0
#XS Ineff= 2 , 0
       0                               0
Bank Sta=9924.011,10075.98
Exp/Cntr=0.3,0.1

Type RM Length L Ch R = 1 ,6448.676,24.572100,24.572100,24.572100
XS GIS Cut Line= 5
1251279.22120547839921.4617271771251225.97270311 839868.66798648
1251224.58186021839867.2307822371251198.68788179839841.024213965
1251170.49738718839815.323235188
#Sta/Elev= 30
9924.016734.93749930.538727.76279935.021723.65689939.641719.59179944.261715.3961
9953.837 706.2929958.121702.68059962.741699.77379971.981695.82999972.476695.5391
9976.601 694.1339977.136693.72219981.221690.00439981.796689.94489995.775691.2934
10000.41692.015710005.01693.045810009.62694.441610014.24696.272410018.85698.4987
10027.74703.042310037.84708.752210041.55711.059510045.99713.339910054.87716.1764
10059.31717.795110066.49   721.110068.19721.771910072.63723.245810075.99724.6255
#Mann= 3 , 0 , 0
9924.016    0.12       09924.016    0.12       010075.99    0.12       0
#XS Ineff= 2 , 0
       0                               0
Bank Sta=9924.016,10075.99
Exp/Cntr=0.3,0.1

Type RM Length L Ch R = 1 ,6424.104,24.572200,24.572200,24.572200
XS GIS Cut Line= 6
1251297.09006535839904.1259285111251274.08663753839883.022867275
1251243.63029514839851.5799932021251242.23945224839850.142788959
1251218.58055359839826.4376224391251186.68781312839799.918117468
#Sta/Elev= 30
9924.008 723.7539932.149713.91389936.601708.84729945.506699.11429949.958694.4569
9953.688690.84399958.346686.67519963.793682.34339967.482679.68039972.049676.9866
9976.617675.3247 9977.94675.02969982.655674.21149987.371673.66369992.086673.4477
9996.802673.432510001.51673.6562 10008.7674.801510013.34 676.19710020.09679.8344
10022.61681.063210024.73681.512710027.24 681.57910029.38681.827510034.02 683.555
10051.13693.953710059.66698.953110063.93700.934110072.46704.534510075.97 706.501
#Mann= 3 , 0 , 0
9924.008    0.12       09924.008    0.12       010075.97    0.12       0
#XS Ineff= 2 , 0
       0                               0
Bank Sta=9924.008,10075.97
Exp/Cntr=0.3,0.1

Type RM Length L Ch R = 1 ,6399.532,24.572100,24.572100,24.572100
XS GIS Cut Line= 6
1251315.00785564839888.759006909 1251281.3688613839859.008295199
1251260.99035044839834.3044403951251243.04424832839813.295881155
1251226.27217573839800.1038535951251204.30365829839786.276021859
#Sta/Elev= 30
9924.066718.47579929.715711.47989941.061697.87479947.234690.19989950.965685.9012
9955.918681.2819 9960.87677.23439965.822672.98479970.524 668.5979974.298665.4299
9979.052662.35269983.316660.82929989.708659.4771   10001657.937510005.17658.2013
10008.91659.343310013.23659.976510017.54660.014510021.86659.659510026.17659.9114
10028.63660.547910038.46664.783810042.64666.897610046.84669.721210054.79675.5326
10058.66678.162410062.54680.167510064.81681.203310066.42681.735610075.93685.9883
#Mann= 3 , 0 , 0
9924.066    0.12       09924.066    0.12       010075.93    0.12       0
#XS Ineff= 2 , 0
       0                10012.94       0
Bank Sta=9924.066,10075.93
Exp/Cntr=0.3,0.1

Type RM Length L Ch R = 1 , 6374.96,24.572100,24.572100,24.572100
XS GIS Cut Line= 6
1251340.51131837839867.3532143071251298.85972825839838.588724215
 1251287.4579738839827.9060216661251275.01653807 839812.88248036
1251267.23788942839806.4851941011251217.38128069 839780.86238949
#Sta/Elev= 30
9924.059705.94569928.298702.39319932.285698.78029936.272694.95729940.259690.9156
9944.247686.61029952.391676.95969958.164670.49749964.182664.61329968.169661.4294
9972.157658.56459976.331655.13859980.827651.68839985.323 649.0119989.744647.1829
9994.077645.9184   10001644.865110009.81644.456210019.88645.102910022.57645.6946
10029.95647.843310037.33650.638710041.02 652.21810048.39655.679810052.08657.8927
10055.77660.944310063.15 667.36610066.84670.315110070.53671.589310075.94672.6969
#Mann= 3 , 0 , 0
9924.059    0.12       09924.059    0.12       010075.94    0.12       0
#XS Ineff= 2 , 0
       0                10011.34       0
Bank Sta=9924.059,10075.94
Exp/Cntr=0.3,0.1

Type RM Length L Ch R = 1 ,6350.388,24.572200,24.572200,24.572200
XS GIS Cut Line= 6
1251366.43439452839813.7782295851251317.38936757839800.990116579
1251300.95766732839799.5169894771251283.27255069 839800.82634308
1251272.52769884839799.1673682281251220.23016162 839779.07469535
#Sta/Elev= 30
9924.074675.17929930.735669.01099934.126666.15759944.297659.63569947.688657.3503
 9964.64645.68119974.759638.36369981.398634.07279984.692 632.1169987.986630.7404
9991.256629.55469994.569628.55619997.857627.989610001.17628.856310004.46630.5577
   10009633.593610014.37636.650310017.69638.145810019.87638.9261 10024.5640.2945
10027.95 641.632 10031.4 643.147 10038.3646.500810048.88652.065910052.44654.0644
   10056656.692410066.69666.148310067.53666.836110070.25668.678610075.95670.1212
#Mann= 3 , 0 , 0
9924.074    0.12       09924.074    0.12       010075.95    0.12       0
#XS Ineff= 2 , 0
       0                10011.23       0
Bank Sta=9924.074,10075.95
Exp/Cntr=0.3,0.1

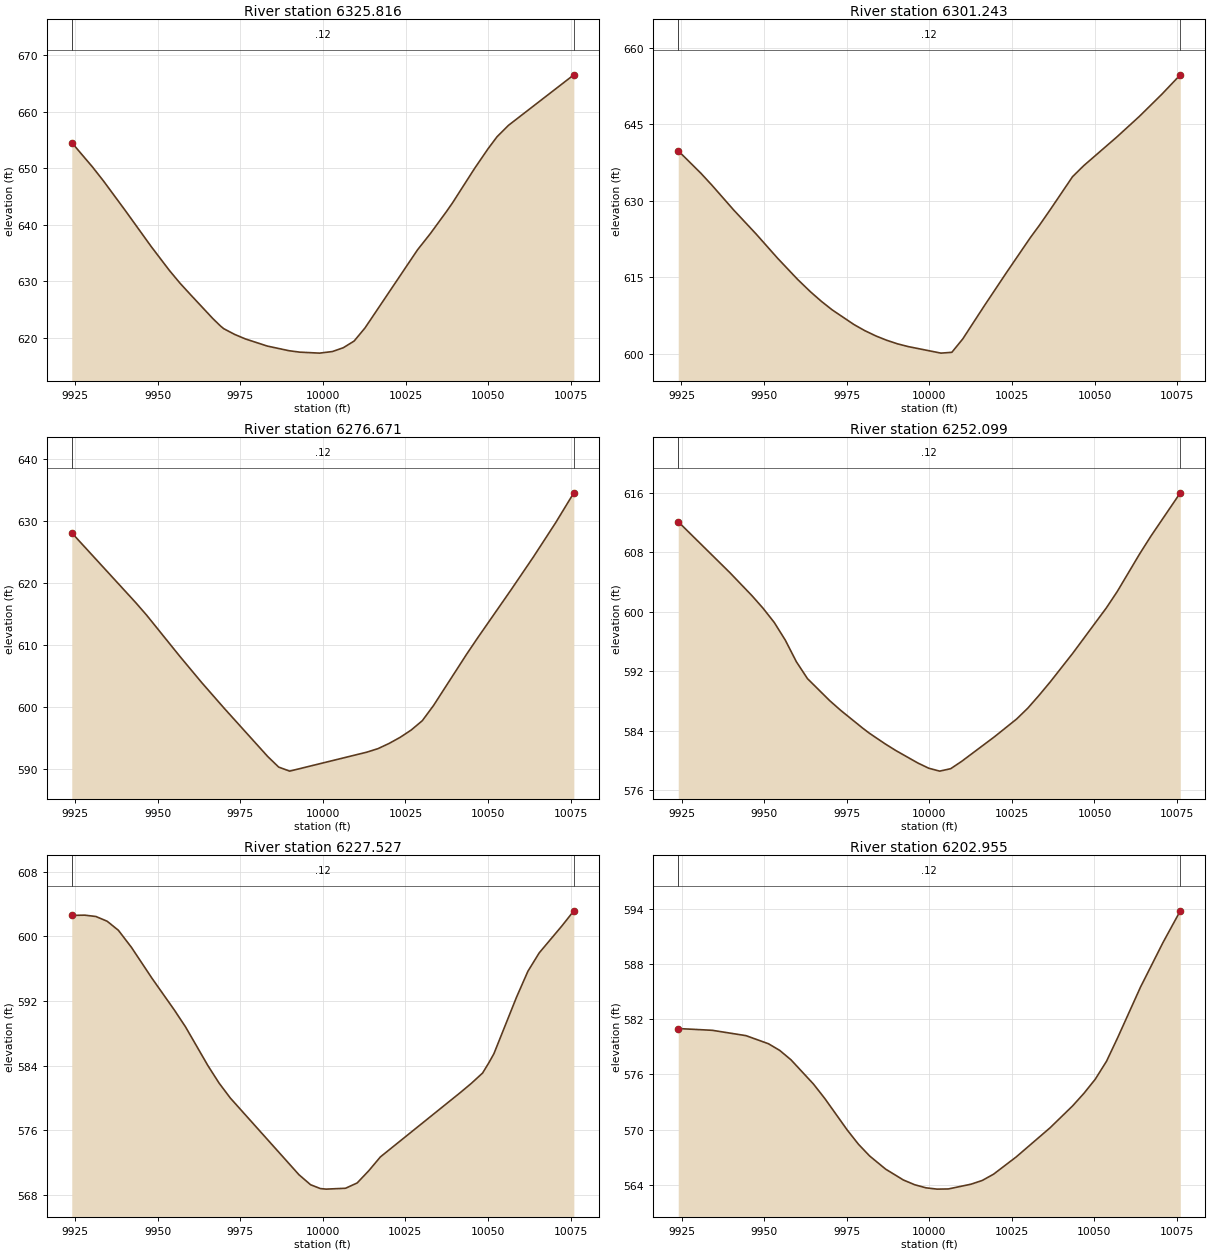
Type RM Length L Ch R = 1 ,6325.816,24.572100,24.572100,24.572100
XS GIS Cut Line= 6
1251362.84404253839780.0972381421251339.23040893839775.860052073
1251318.28829655839774.0745981011251258.82598772839777.463637461
 1251237.8846754839773.419962428 1251213.3368144 839764.99944174
#Sta/Elev= 30
9924.049654.49839930.283650.21339933.616647.73289940.283642.4425 9948.04 636.133
9953.548631.90049956.841629.58659960.133627.49049966.719623.35959969.058622.0328
 9970.01621.57119973.298 620.5629976.586619.75199983.162618.49959989.738617.6746
9993.026617.4177    9999617.245910002.89617.527910006.18618.202810009.46619.3903
10012.75 621.71210028.62 635.52310032.52638.410710037.43642.3444 10039.2643.8321
10045.88649.930910049.95653.409110052.66655.532410056.13657.5558 10075.9666.4944
#Mann= 3 , 0 , 0
9924.049    0.12       09924.049    0.12       0 10075.9    0.12       0
#XS Ineff= 2 , 0
       0                               0
Bank Sta=9924.049,10075.9
Exp/Cntr=0.3,0.1

Type RM Length L Ch R = 1 ,6301.243,24.572200,24.572200,24.572200
XS GIS Cut Line= 6
 1251360.2503883839759.8027238781251324.47239508839754.608562617
1251285.74014071 839751.848046261251283.74887226 839751.66136485
1251254.31269588839748.9741942831251210.14475017839738.573836465
#Sta/Elev= 30
9924.016639.80049930.911635.37589934.226633.05399940.857628.16519947.487623.5807
9954.118618.74369960.169614.60869964.033612.19949967.322610.33599970.611608.6573
9977.189605.79039980.479604.59389983.768603.57599987.057602.72249990.346602.0181
9993.635601.472710003.51600.1972 10006.8600.3549 10010.1602.970610016.69609.5219
10023.28615.909510030.56622.807810033.22625.146310036.59628.287410043.33634.7361
 10046.7636.880810056.69642.478710063.56646.5425 10070.3650.836610075.93654.6655
#Mann= 3 , 0 , 0
9924.016    0.12       09924.016    0.12       010075.93    0.12       0
#XS Ineff= 2 , 0
       0                               0
Bank Sta=9924.016,10075.93
Exp/Cntr=0.3,0.1

Type RM Length L Ch R = 1 ,6276.671,24.572100,24.572100,24.572100
XS GIS Cut Line= 5
1251365.93269784839740.980269833 1251292.0256428839728.255236478
1251290.04398246839727.9850101271251282.86241503839726.743246003
1251216.81805199839711.904849046
#Sta/Elev= 22
9924.005628.10439943.353616.86029946.682614.8225 9956.67608.22259963.328603.9663
9970.192599.78869983.303592.04819986.632590.33359989.961589.6814 10013.3592.7372
10016.67593.301810020.03594.137510023.39 595.12510026.76596.311810030.12597.8188
10033.48600.241510043.57608.569710046.93611.219310057.02618.953510063.74624.2223
10070.47 629.73710075.98634.5589
#Mann= 3 , 0 , 0
9924.005    0.12       09924.005    0.12       010075.98    0.12       0
#XS Ineff= 2 , 0
       0                               0
Bank Sta=9924.005,10075.98
Exp/Cntr=0.3,0.1

Type RM Length L Ch R = 1 ,6252.099,24.572100,24.572100,24.572100
XS GIS Cut Line= 6
1251368.72667002 839718.49749677  1251312.179598839706.473536658
1251295.19421264839703.8727764751251293.20845896839703.634486091
1251270.65347569839699.8669305741251220.10483218839687.183856516
#Sta/Elev= 30
9924.005612.12929939.647605.26849946.355602.15369949.709600.46129953.064598.5634
9956.418596.17789959.772593.26579963.126 590.9959969.835588.03569973.189586.7182
9979.782584.34539981.817583.65359986.555582.22979989.874581.30579996.513579.6327
9999.828578.925610003.15578.532810006.47578.8615 10009.8579.850410019.78583.1799
10026.47585.568110029.86587.036310033.24588.753510036.62590.558210043.39594.3919
10053.53600.483710056.92602.749610063.68607.804610067.06610.178110075.98616.0265
#Mann= 3 , 0 , 0
9924.005    0.12       09924.005    0.12       010075.98    0.12       0
#XS Ineff= 2 , 0
       0                               0
Bank Sta=9924.005,10075.98
Exp/Cntr=0.3,0.1

Type RM Length L Ch R = 1 ,6227.527,24.572200,24.572200,24.572200
XS GIS Cut Line= 6
1251373.63533121839701.5775423631251321.17250536839687.985466604
1251301.68769148 839680.754199351251299.86006838839679.941922411
1251280.48325412839672.4120425011251228.54770982839656.912856078
#Sta/Elev= 30
9924.022602.58519927.951602.6156 9931.34602.4488 9934.73601.86469938.119600.7512
9942.058598.65119948.286594.82469955.064590.89389958.454588.80679965.232584.0154
9968.621581.8506 9972.01580.01189992.805570.52379996.305569.29369999.257568.8209
   10001568.749910006.89568.857410010.41 569.51310013.93571.029110017.45572.7373
10041.53580.652110044.96581.820610048.38583.106710050.34584.4214 10051.8585.4925
10058.65592.483610062.08595.6752 10065.5597.947610072.35601.273610075.99 603.151
#Mann= 3 , 0 , 0
9924.022    0.12       09924.022    0.12       010075.99    0.12       0
#XS Ineff= 2 , 0
       0                               0
Bank Sta=9924.022,10075.99
Exp/Cntr=0.3,0.1

Type RM Length L Ch R = 1 ,6202.955,24.572100,24.572100,24.572100
XS GIS Cut Line= 4
1251383.05119291839677.6270018361251310.74710874839657.723602743
1251308.80062953839657.2640173781251236.87257915839636.024536782
#Sta/Elev= 30
9924.006580.97629934.315580.78539944.524580.2054 9951.33579.32419954.732578.6022
9958.135 577.5839964.941574.94979968.344573.3958 9975.15 569.9659978.552568.4142
9981.955567.13349986.787565.70659992.164564.52599995.567564.0122 9998.97563.6761
10002.36563.533110005.78563.552410012.62564.066410016.04564.474110019.47565.1569
10026.31567.027810036.57570.194210043.41572.580710046.83573.941910050.25575.4723
10053.67577.428210057.09580.027510063.94585.472110070.78 590.335   10076593.7642
#Mann= 3 , 0 , 0
9924.006    0.12       09924.006    0.12       0   10076    0.12       0
#XS Ineff= 2 , 0
       0                               0
Bank Sta=9924.006,10076
Exp/Cntr=0.3,0.1

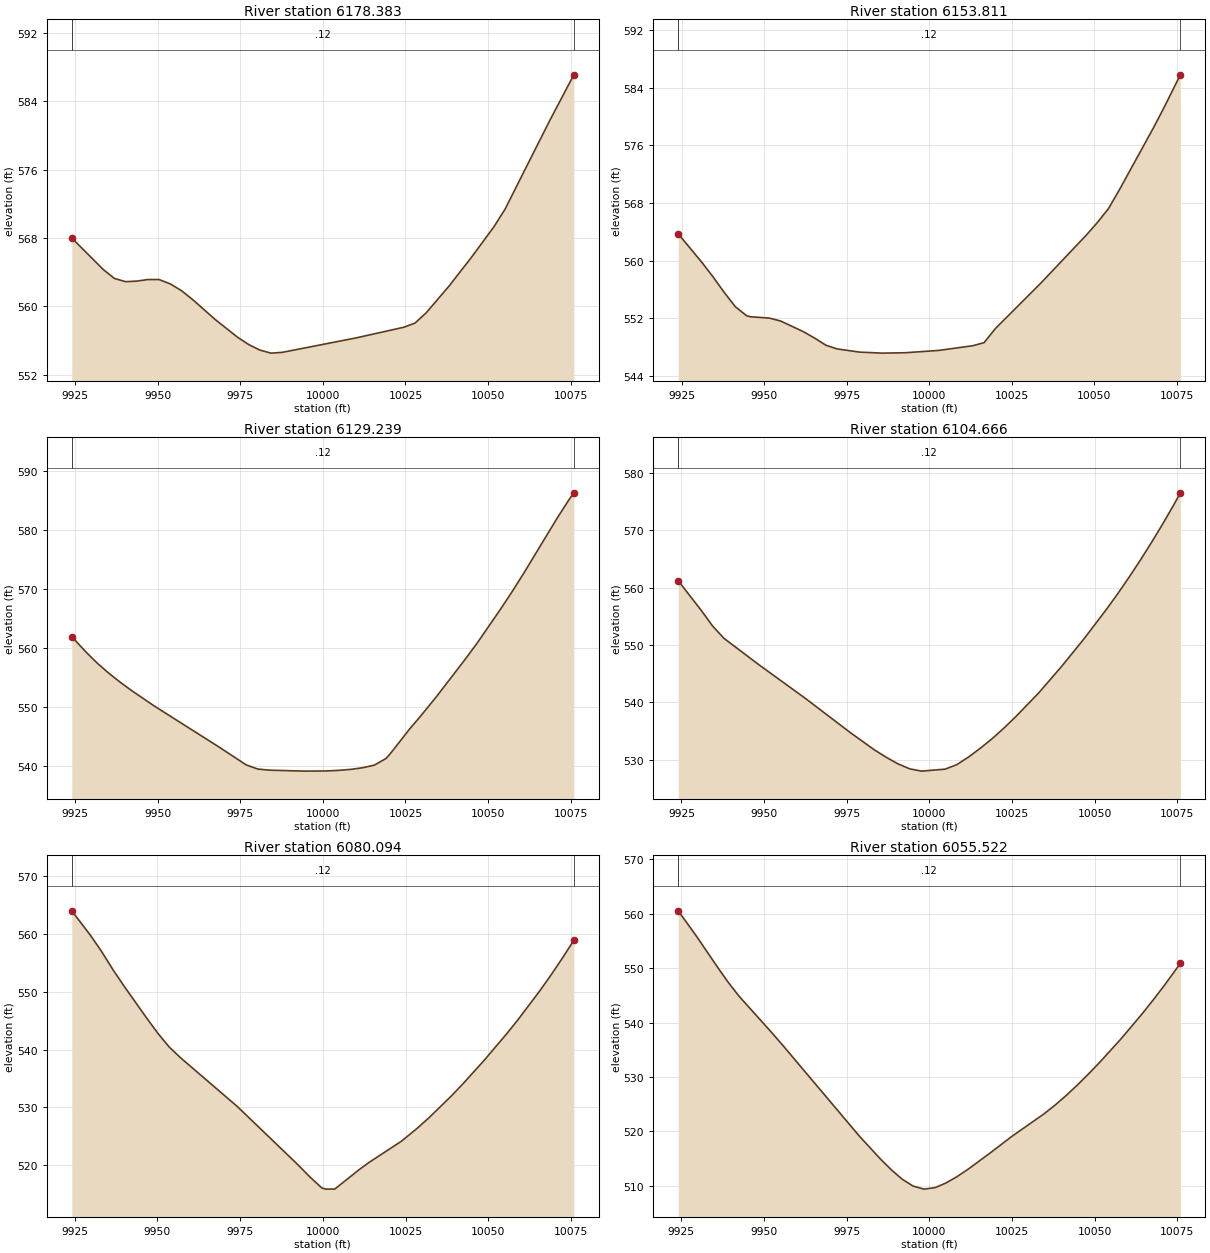
Type RM Length L Ch R = 1 ,6178.383,24.572200,24.572200,24.572200
XS GIS Cut Line= 6
1251388.85705242839651.6973004091251336.44241706 839637.89483323
1251316.07929442839633.6863571631251314.10993417839633.337616287
1251289.50992689839628.0671278091251241.45572485839614.866474964
#Sta/Elev= 26
9924.005567.99419933.501564.32199936.894 563.2679940.287562.88469943.679562.9506
9947.072 563.1369950.465563.13089953.857562.6205 9957.25561.82649960.643560.7744
9967.428 558.4619974.213556.38129977.606555.52379980.964554.88249984.314554.5287
9987.664554.614810010.07556.308310024.54557.557710027.92558.044210031.32559.2541
10038.21562.372210044.93565.700510051.74569.272710055.14571.344510068.75581.7717
10075.99587.0767
#Mann= 3 , 0 , 0
9924.005    0.12       09924.005    0.12       010075.99    0.12       0
#XS Ineff= 2 , 0
       0                               0
Bank Sta=9924.005,10075.99
Exp/Cntr=0.3,0.1

Type RM Length L Ch R = 1 ,6153.811,24.572100,24.572100,24.572100
XS GIS Cut Line= 4
1251392.98399329839631.0850195821251321.06330121839609.824643038
1251319.16840987839609.1848095971251247.25718208  839587.8943749
#Sta/Elev= 28
9924.003563.7072 9931.04559.81769934.461557.78079937.882555.59939941.303553.5785
9944.725552.32349945.906552.18249951.567552.00479954.988551.60039961.831550.1295
9965.252549.23579968.673548.23999972.094547.72179978.936547.27449985.779547.1346
9992.621547.186110002.91547.512410013.17 548.162 10016.6548.593810020.02550.5471
 10033.7556.828610047.39563.456310050.81565.230610054.23567.190910057.65569.9032
10067.92578.480110071.34  581.49   10076585.7986
#Mann= 3 , 0 , 0
9924.003    0.12       09924.003    0.12       0   10076    0.12       0
#XS Ineff= 2 , 0
       0                               0
Bank Sta=9924.003,10076
Exp/Cntr=0.3,0.1

Type RM Length L Ch R = 1 ,6129.239,24.572100,24.572100,24.572100
XS GIS Cut Line= 6
1251400.21120681839611.7732313651251357.83590739839598.046555015
1251329.52273859839586.8575451921251327.68444853839586.069706595
1251296.47658642839573.9284821311251256.81571212839561.719745595
#Sta/Elev= 30
9924.013561.84619928.358559.20579931.806557.31179935.255555.63599938.704554.1072
9942.152552.6926 9949.05550.06399968.556543.14289976.824540.09829980.352539.3939
 9983.88539.21069994.463539.0463   10001539.073310005.06 539.18210008.58539.3493
 10012.1539.623210015.62540.068310019.14541.194310020.65542.160410026.18546.1221
 10029.7548.445110034.49551.739110043.55558.343110046.99560.973910053.85566.5521
10057.28569.454610060.72 572.50210071.02582.017810074.45585.005110075.98586.2266
#Mann= 3 , 0 , 0
9924.013    0.12       09924.013    0.12       010075.98    0.12       0
#XS Ineff= 2 , 0
       0                               0
Bank Sta=9924.013,10075.98
Exp/Cntr=0.3,0.1

Type RM Length L Ch R = 1 ,6104.666,24.572200,24.572200,24.572200
XS GIS Cut Line= 6
1251409.20013227839590.5067950981251372.47223752839578.577905117
 1251339.0725274839564.2005603941251337.22191713839563.442113559
1251306.26684289839550.6689591451251266.40324661839539.187526075
#Sta/Elev= 30
9924.021561.20259930.919 556.0789934.368553.34149937.818 551.1759948.166546.6598
9962.637540.61349976.228 534.6489983.372 531.6979986.944 530.4039990.516529.2548
9994.088528.37639997.659527.979410004.76 528.32310008.31529.100410011.86530.4331
10015.41 531.95810018.96533.613610022.51535.445610026.06537.421510033.16541.6545
10040.04546.249310046.87551.101610053.69556.271410057.11559.002310060.52561.8612
10063.94564.854210067.35567.973310070.76571.222610074.18574.638710075.97576.5437
#Mann= 3 , 0 , 0
9924.021    0.12       09924.021    0.12       010075.97    0.12       0
#XS Ineff= 2 , 0
       0                               0
Bank Sta=9924.021,10075.97
Exp/Cntr=0.3,0.1

Type RM Length L Ch R = 1 ,6080.094,24.572100,24.572100,24.572100
XS GIS Cut Line= 6
1251421.14123079 839568.288265111251373.13265585839554.264151981
1251350.90639519839543.037506728 1251349.2218524 839541.95939933
1251328.67640223839532.0413191341251277.82082921839520.815212565
#Sta/Elev= 30
9924.084563.99989929.687559.80279933.105556.96719936.523553.83359939.941550.9362
9946.777545.40689950.195542.75159953.613540.39669957.031538.54859974.099530.1615
9992.128520.25489996.176517.90439999.339516.23489999.902 516.002   10001515.8459
10003.62 515.861 10010.9519.185410014.03 520.48910023.81524.155510028.71526.4626
10032.07528.186110038.79531.932710042.15533.938210048.86 538.18610055.58542.7205
10058.94545.112910065.66550.203810069.02 552.92210072.38555.775710075.89558.8896
#Mann= 3 , 0 , 0
9924.084    0.12       09924.084    0.12       010075.89    0.12       0
#XS Ineff= 2 , 0
       0                               0
Bank Sta=9924.084,10075.89
Exp/Cntr=0.3,0.1

Type RM Length L Ch R = 1 ,6055.522,24.572200,24.572200,24.572200
XS GIS Cut Line= 6
 1251434.1671626839522.3670645141251379.55649116839518.673364702
1251359.41104769839520.1876156121251357.47076269839520.672686858
1251344.63566642839521.514626673 1251283.0028644839514.125433103
#Sta/Elev= 30
9924.062560.52739929.355556.05759935.932550.1952 9939.22547.35479942.508544.8052
9952.373538.12999955.662535.82699978.798519.1624 9985.26514.8937 9988.55512.9135
 9991.84511.1861 9995.13509.93429998.421509.377710001.76509.651810005.05510.5094
10008.34511.648210011.63512.987810018.23515.932810024.83519.003910034.75523.2271
10038.05524.816610041.36526.556210044.66528.430110047.96530.415710051.27532.4947
10057.88536.908510064.49541.671610067.79544.192510071.09546.808310075.94550.8551
#Mann= 3 , 0 , 0
9924.062    0.12       09924.062    0.12       010075.94    0.12       0
#XS Ineff= 2 , 0
       0                               0
Bank Sta=9924.062,10075.94
Exp/Cntr=0.3,0.1