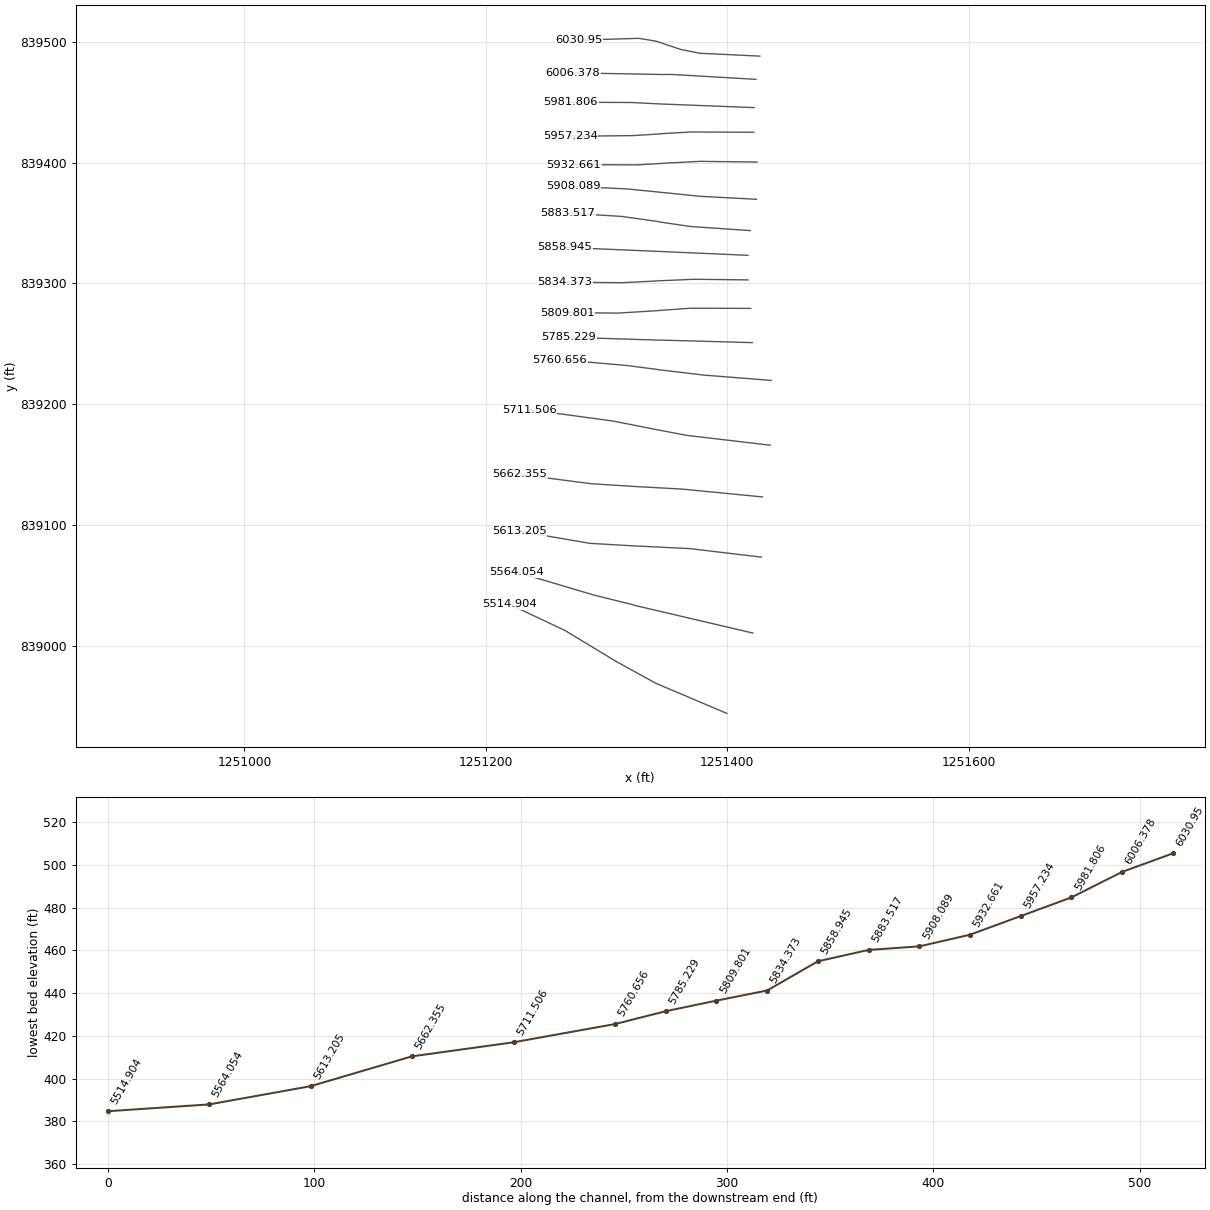
HEC-RAS study 77_ras.prj: 77

--- 77_ras.g01 (geometry) --- (continued)

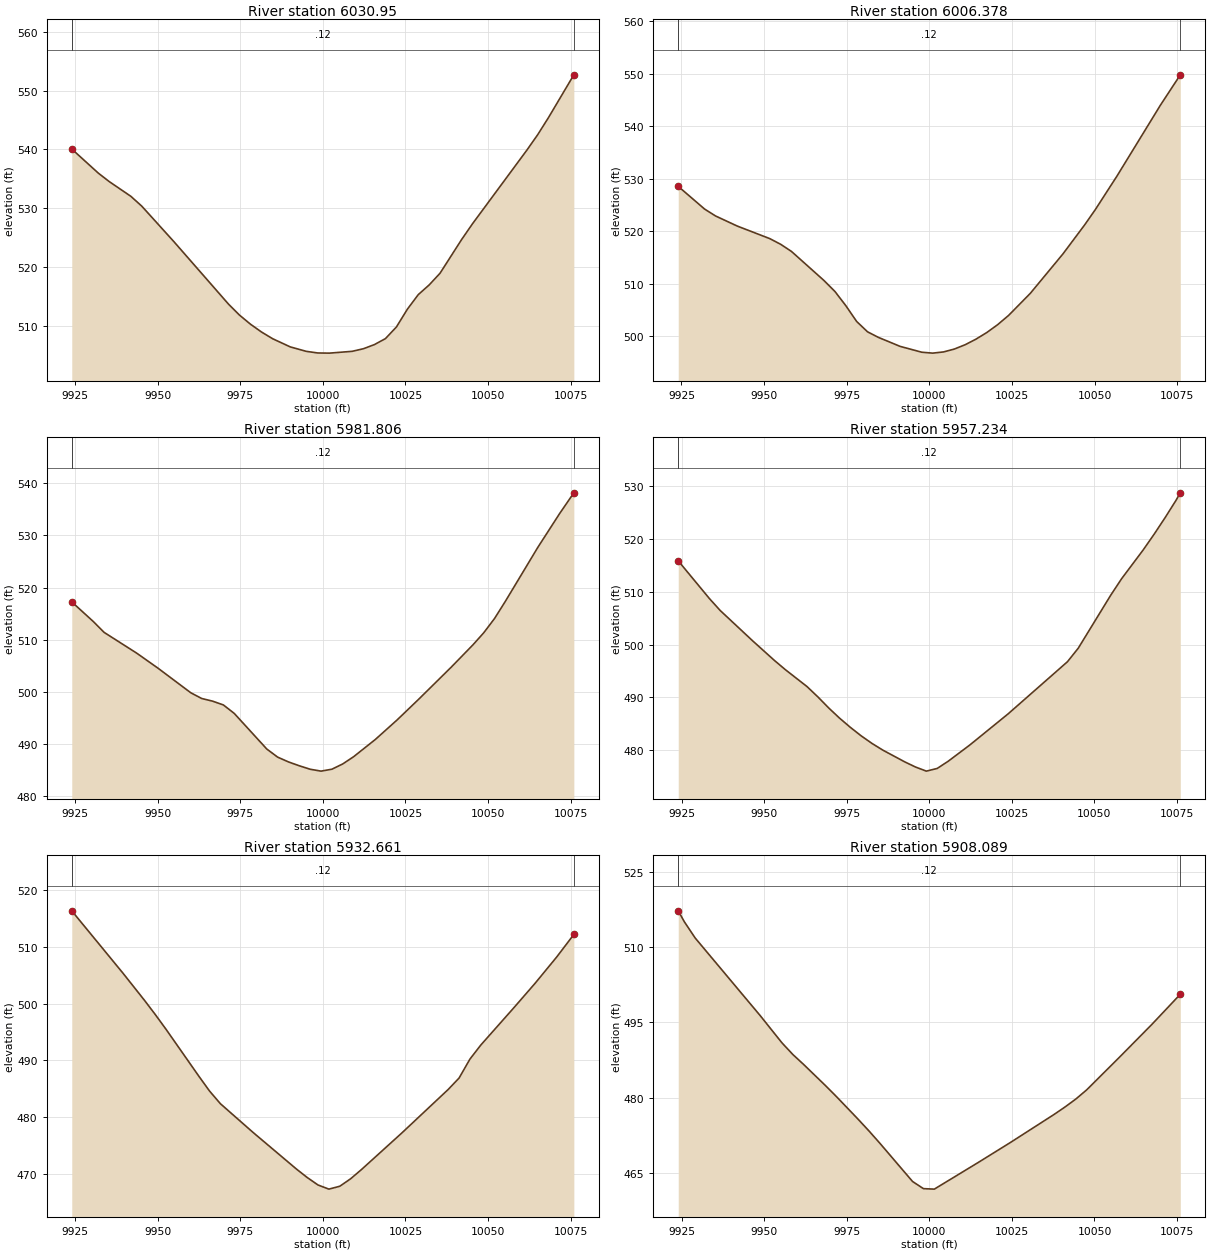
Type RM Length L Ch R = 1 , 6030.95,24.572100,24.572100,24.572100
XS GIS Cut Line= 6
1251427.04975168839488.0755653131251377.17925106839490.464472195
1251361.29916062839493.6435280491251340.95524167839500.465411802
1251326.67989341 839502.80964952 1251276.9129007839501.295813725
#Sta/Elev= 30
9924.063540.05899932.078535.97569935.362 534.5439941.932532.02969945.216530.3719
 9955.07 524.2559971.493513.70159974.792511.85099978.138510.29569981.484508.9635
 9984.83 507.832 9990.18506.43899995.025505.68499998.483505.409710002.01505.3832
10008.89505.688710012.31506.132310015.64506.837510018.96507.848810022.29509.8324
10025.61512.8595 10028.9515.325510032.18516.963110035.46518.942410042.03524.7006
10045.31527.368710061.75539.872610065.04542.507410068.33545.439110075.96552.6673
#Mann= 3 , 0 , 0
9924.063    0.12       09924.063    0.12       010075.96    0.12       0
#XS Ineff= 2 , 0
       0                               0
Bank Sta=9924.063,10075.96
Exp/Cntr=0.3,0.1

Type RM Length L Ch R = 1 ,6006.378,24.572100,24.572100,24.572100
XS GIS Cut Line= 5
1251423.74550929839468.8597302791251354.90674562 839472.84777911
1251348.88379916839472.907271975 1251346.8844563839472.856006776
1251271.93210026839474.228913485
#Sta/Elev= 30
9924.023 528.5259932.018524.19249935.305522.88659941.877520.95859951.736518.5597
9955.023 517.4799958.309516.10849968.168510.54969971.454508.47189974.741505.7713
9978.027  502.759981.313 500.785  9984.6499.71979991.172498.00549997.737496.8891
10001.02496.7181 10004.3496.944110007.58497.495910010.86498.323910014.14499.3881
10017.43500.660610020.71502.158410023.99503.907310030.55508.1094 10040.4515.6098
10046.96521.135910050.24524.0963 10056.8530.499910069.93544.007210075.96549.8066
#Mann= 3 , 0 , 0
9924.023    0.12       09924.023    0.12       010075.96    0.12       0
#XS Ineff= 2 , 0
       0                               0
Bank Sta=9924.023,10075.96
Exp/Cntr=0.3,0.1

Type RM Length L Ch R = 1 ,5981.806,24.572200,24.572200,24.572200
XS GIS Cut Line= 5
1251422.26473439839445.4685536431251347.33092841839448.369347556
1251345.33229874839448.4433709351251320.27742335  839449.6886583
1251270.37027354839449.938016583
#Sta/Elev= 30
 9924.01517.24519930.517513.4849  9933.8511.3977 9943.65507.41939950.216504.4802
9960.066499.8007 9963.35  498.719966.633498.20369969.916 497.4719973.199495.8448
9983.049489.01569986.333487.46279989.616486.54199992.899485.80029996.182485.1386
9999.466484.777210002.75485.144610006.03486.154910009.32487.539910015.89490.8443
10022.46494.578810029.03 498.57310038.87504.721810045.43 508.99210048.71511.3135
10051.99514.062710055.27517.366610065.11527.728910071.68 534.18510075.99538.1703
#Mann= 3 , 0 , 0
 9924.01    0.12       0 9924.01    0.12       010075.99    0.12       0
#XS Ineff= 2 , 0
       0                               0
Bank Sta=9924.01,10075.99
Exp/Cntr=0.3,0.1

Type RM Length L Ch R = 1 ,5957.234,24.572100,24.572100,24.572100
XS GIS Cut Line= 6
1251421.93302587839425.0560921031251369.81254344839425.274002038
1251346.97971445839423.9934808171251344.99396076839423.755190433
1251322.17083523839422.2887089121251270.05199272839421.726816737
#Sta/Elev= 30
 9924.01515.82959933.461508.68669936.742 506.4199946.585500.67019953.146496.9781
9956.427495.24939962.989492.0497 9966.27490.10319969.551488.00689972.832486.0807
9976.112484.33349979.398482.72129982.684481.2809 9985.97480.01619992.542477.8122
9995.828476.83079999.115476.051110002.41476.5614 10005.7 477.90710012.27480.9941
10023.87 486.88410041.83 496.74510045.11499.315210054.95  509.3510058.23512.4558
10064.79517.924710068.08520.878910071.36523.973510074.64527.225110075.99528.6955
#Mann= 3 , 0 , 0
 9924.01    0.12       0 9924.01    0.12       010075.99    0.12       0
#XS Ineff= 2 , 0
       0                               0
Bank Sta=9924.01,10075.99
Exp/Cntr=0.3,0.1

Type RM Length L Ch R = 1 ,5932.661,24.572200,24.572200,24.572200
XS GIS Cut Line= 6
1251424.65470816839400.4349216961251377.33980909 839400.96394692
1251349.70423876839399.5460281391251347.71245234839399.364956706
1251324.88145004839398.0135564961251272.76100049839398.275967386
#Sta/Elev= 25
 9924.01516.33199939.465 505.3839946.027500.56449949.308498.05189952.589495.4315
9962.432487.24189965.713484.59489968.994482.36499978.846477.32329991.987470.8676
9995.272469.36599998.557468.041910001.85 467.31510005.14467.823310008.42469.1351
10011.71470.766610023.87477.176410037.98484.881710041.26486.889210044.54490.2179
10047.82492.688110057.66499.146110064.22503.539510070.79 508.19110075.99512.1704
#Mann= 3 , 0 , 0
 9924.01    0.12       0 9924.01    0.12       010075.99    0.12       0
#XS Ineff= 2 , 0
       0                               0
Bank Sta=9924.01,10075.99
Exp/Cntr=0.3,0.1

Type RM Length L Ch R = 1 ,5908.089,24.572100,24.572100,24.572100
XS GIS Cut Line= 6
1251424.17004142839369.5619165191251376.87210792839372.059918528
1251349.38746422839374.8962050581251347.39738984839375.095212555
1251317.10531368839378.132490052 1251272.6022649839380.154705338
#Sta/Elev= 24
9924.006 517.1989925.853515.02639929.139511.79339948.851496.34029955.422490.9386
9958.708488.62949961.993486.63699968.564482.46279971.851480.29569978.448475.7751
9981.746473.43689985.044470.98949994.939463.38549998.237461.962810001.53461.8676
10014.72 467.12610024.62471.162910037.78476.715410041.06478.184110044.35479.7692
10047.63481.592710057.48 488.03110067.34494.589310075.99500.6123
#Mann= 3 , 0 , 0
9924.006    0.12       09924.006    0.12       010075.99    0.12       0
#XS Ineff= 2 , 0
       0                               0
Bank Sta=9924.006,10075.99
Exp/Cntr=0.3,0.1

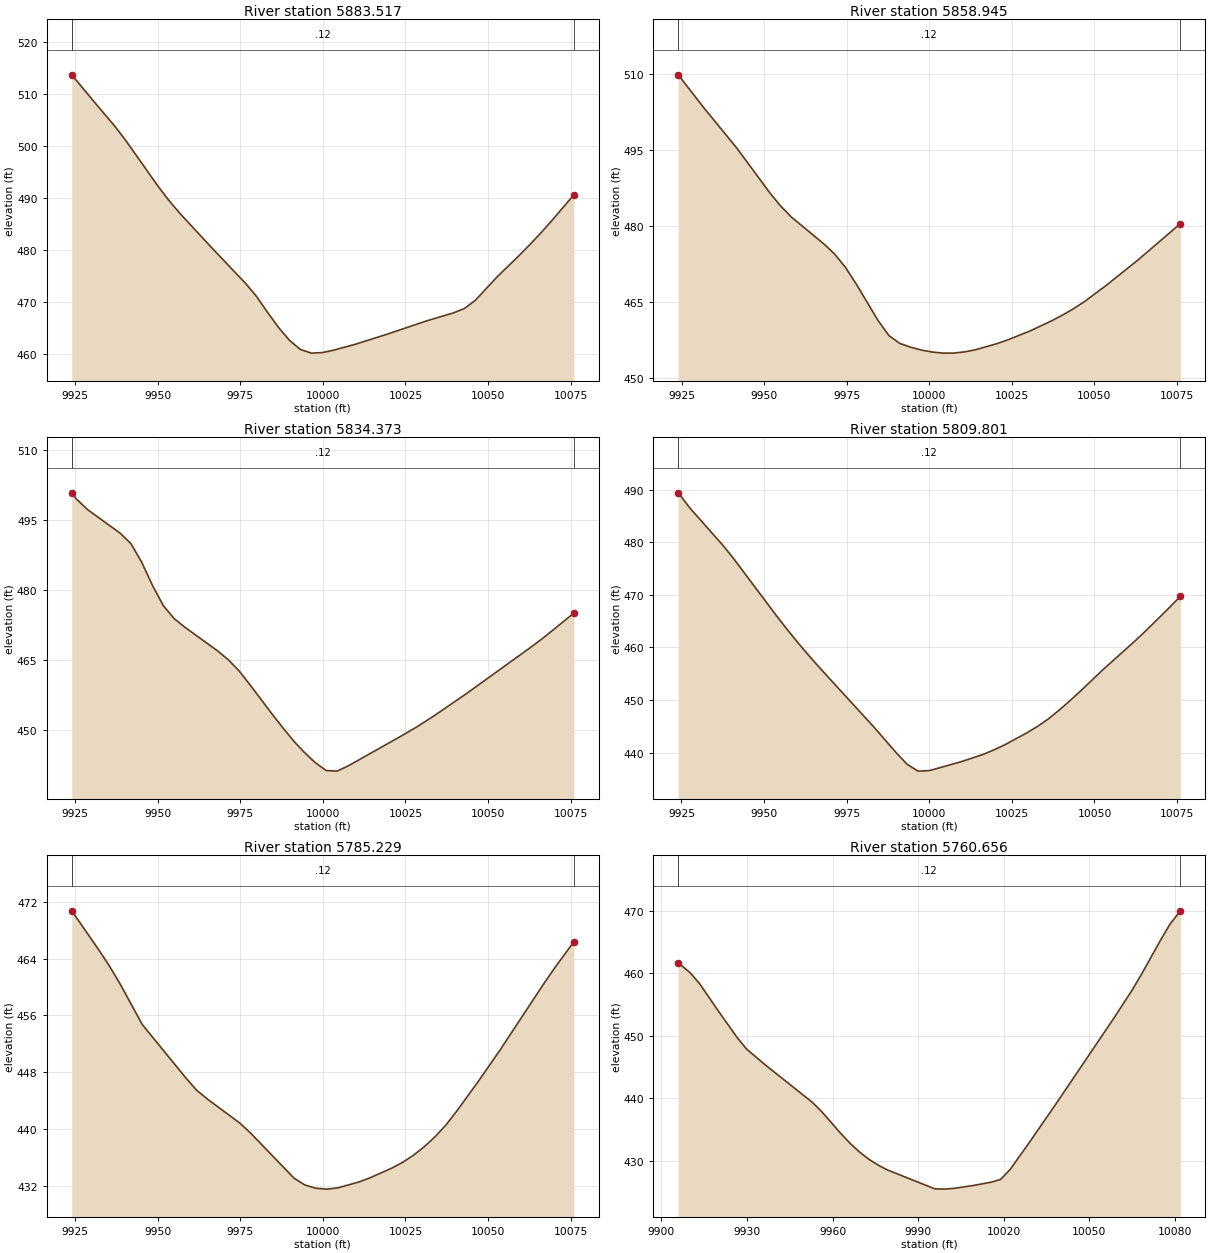
Type RM Length L Ch R = 1 ,5883.517,24.572100,24.572100,24.572100
XS GIS Cut Line= 6
1251419.03224412839343.6540473881251369.32048467839347.047598884
1251344.43520144839350.7280387141251342.48282733839351.161899687
1251312.42548946839355.3885305131251267.88099523839358.121583087
#Sta/Elev= 29
9924.017 513.6729930.582 508.6469937.159503.71399940.447500.98089950.313492.1098
9953.601489.3955 9956.89486.94929966.755 480.1899976.644473.58769979.961471.0756
9983.277468.03299986.594465.1337 9989.91462.65529993.227460.89589996.543460.1978
9999.871460.3038 10003.2460.752410009.83 461.89710019.77463.896310031.35466.3797
10039.58467.935410042.87468.777410046.15 470.33610052.73474.8338 10059.3478.8821
10062.59 481.00410065.88483.212410069.16485.547410075.98490.6171
#Mann= 3 , 0 , 0
9924.017    0.12       09924.017    0.12       010075.98    0.12       0
#XS Ineff= 2 , 0
       0                               0
Bank Sta=9924.017,10075.98
Exp/Cntr=0.3,0.1

Type RM Length L Ch R = 1 ,5858.945,24.572200,24.572200,24.572200
XS GIS Cut Line= 4
1251417.12910616839323.1820072211251342.20136956839326.453297599
1251340.20325725839326.5401721081251265.27228518839329.736246502
#Sta/Elev= 30
9924.001509.90669931.936503.24429941.788495.3764 9951.64486.65059954.924484.0219
9958.208481.8082 9968.06476.48599971.344474.46889974.628471.82999977.912468.5134
 9984.48461.34239987.764458.35069991.047456.80469994.331 456.0539997.615 455.478
 10000.9455.085710004.18454.869910007.47454.877910010.75455.118310014.03455.5388
 10020.6456.766510023.89457.520510030.45459.240810037.02461.250910040.31462.3816
10043.59463.623910046.87465.007110053.44   468.210063.29473.3486   10076480.4696
#Mann= 3 , 0 , 0
9924.001    0.12       09924.001    0.12       0   10076    0.12       0
#XS Ineff= 2 , 0
       0                               0
Bank Sta=9924.001,10076
Exp/Cntr=0.3,0.1

Type RM Length L Ch R = 1 ,5834.373,24.572100,24.572100,24.572100
XS GIS Cut Line= 6
1251417.25657948839302.8236864861251372.71078025839303.349786577
1251342.29644775839302.0438851141251340.30233877839301.890492175
1251312.65974865839300.5240426191251265.34652046839300.882211464
#Sta/Elev= 29
9924.009500.85479925.502499.47359928.783497.26439938.627492.22119941.908489.9717
9945.189485.9747 9948.47480.96789951.751476.63929955.032 473.8799958.313472.0134
9968.156466.9773 9971.44465.05699974.724462.62999978.007 459.6669984.575453.5137
9987.859  450.539991.143447.70329994.427445.20669997.711443.0307   10001441.3314
10004.28441.203310007.57442.280110023.99448.825910028.68450.784410033.84453.1303
10043.68457.918110063.37467.969510066.65469.712710075.99475.0662
#Mann= 3 , 0 , 0
9924.009    0.12       09924.009    0.12       010075.99    0.12       0
#XS Ineff= 2 , 0
       0                               0
Bank Sta=9924.009,10075.99
Exp/Cntr=0.3,0.1

Type RM Length L Ch R = 1 ,5809.801,24.572200,24.572200,24.572200
XS GIS Cut Line= 6
1251419.38803441839279.2454350161251369.56124724839279.370648404
1251344.46489762839277.5922149641251342.47482323839277.393207583
1251309.05607067839275.3209811371251267.55743199839275.803079969
#Sta/Elev= 30
9924.014489.36769927.639 486.4139937.481479.43099940.762476.88079953.886465.8905
9957.166463.25939960.447460.72829963.728458.30019967.009455.98099983.437444.7063
9990.015439.94599993.304437.76039996.593436.46489999.885436.5566   10001436.7309
10009.75438.273810016.32439.650210019.61440.5119 10022.9441.487210029.47443.7168
10032.76444.970310036.04446.396210039.32448.055610042.61449.870410045.89451.7571
10052.45455.682610062.29461.226110065.57463.164210072.14467.215310075.98469.6954
#Mann= 3 , 0 , 0
9924.014    0.12       09924.014    0.12       010075.98    0.12       0
#XS Ineff= 2 , 0
       0                               0
Bank Sta=9924.014,10075.98
Exp/Cntr=0.3,0.1

Type RM Length L Ch R = 1 ,5785.229,24.572100,24.572100,24.572100
XS GIS Cut Line= 4
1251420.68582974839250.8990266441251345.72265728839252.983055135
1251343.72265728839252.9830551941251268.76845563 839255.28732247
#Sta/Elev= 30
9924.008470.75329932.215465.22959935.497462.90819938.779460.33259945.343454.7224
9958.471447.23449961.754 445.4829965.036444.22159974.882 440.8229978.164439.4042
9991.293 433.0529994.575432.09059997.857431.637910001.14431.509410004.42431.6711
10010.99 432.52610014.27433.101810020.83434.462810024.11435.2684 10027.4436.2742
10030.68437.479410033.96438.879810037.24440.536310038.71441.411810040.53442.5017
10047.09446.716210053.66451.128210066.79460.403510070.07462.622910075.99466.3881
#Mann= 3 , 0 , 0
9924.008    0.12       09924.008    0.12       010075.99    0.12       0
#XS Ineff= 2 , 0
       0                               0
Bank Sta=9924.008,10075.99
Exp/Cntr=0.3,0.1

Type RM Length L Ch R = 1 ,5760.656,49.150500,49.150500,49.150500
XS GIS Cut Line= 6
1251436.42212957839219.6229905191251380.23218039 839224.05847165
1251343.73745552839228.4097021221251341.76297328839228.728167042
1251316.81323427839231.9681662021251261.19142514839236.852876961
#Sta/Elev= 30
9905.882461.7288 9910.15460.08019913.441 458.3259920.023453.95699926.605449.7189
9929.896447.89269936.479445.35489952.934439.38599956.225437.89819962.809434.4527
9966.113432.85449969.417431.46059972.721430.29169976.025429.33279979.329428.5599
 9995.85425.5513    9999425.501510002.47425.616110009.09426.0582 10015.7426.6163
10019.01427.062910022.32428.657810028.93432.889410038.81439.420610058.57452.7676
10065.15457.374810068.45459.921210075.03465.304310078.33467.8466   10082470.0223
#Mann= 3 , 0 , 0
9905.882    0.12       09905.882    0.12       0   10082    0.12       0
#XS Ineff= 2 , 0
       09978.155                       0
Bank Sta=9905.882,10082
Exp/Cntr=0.3,0.1

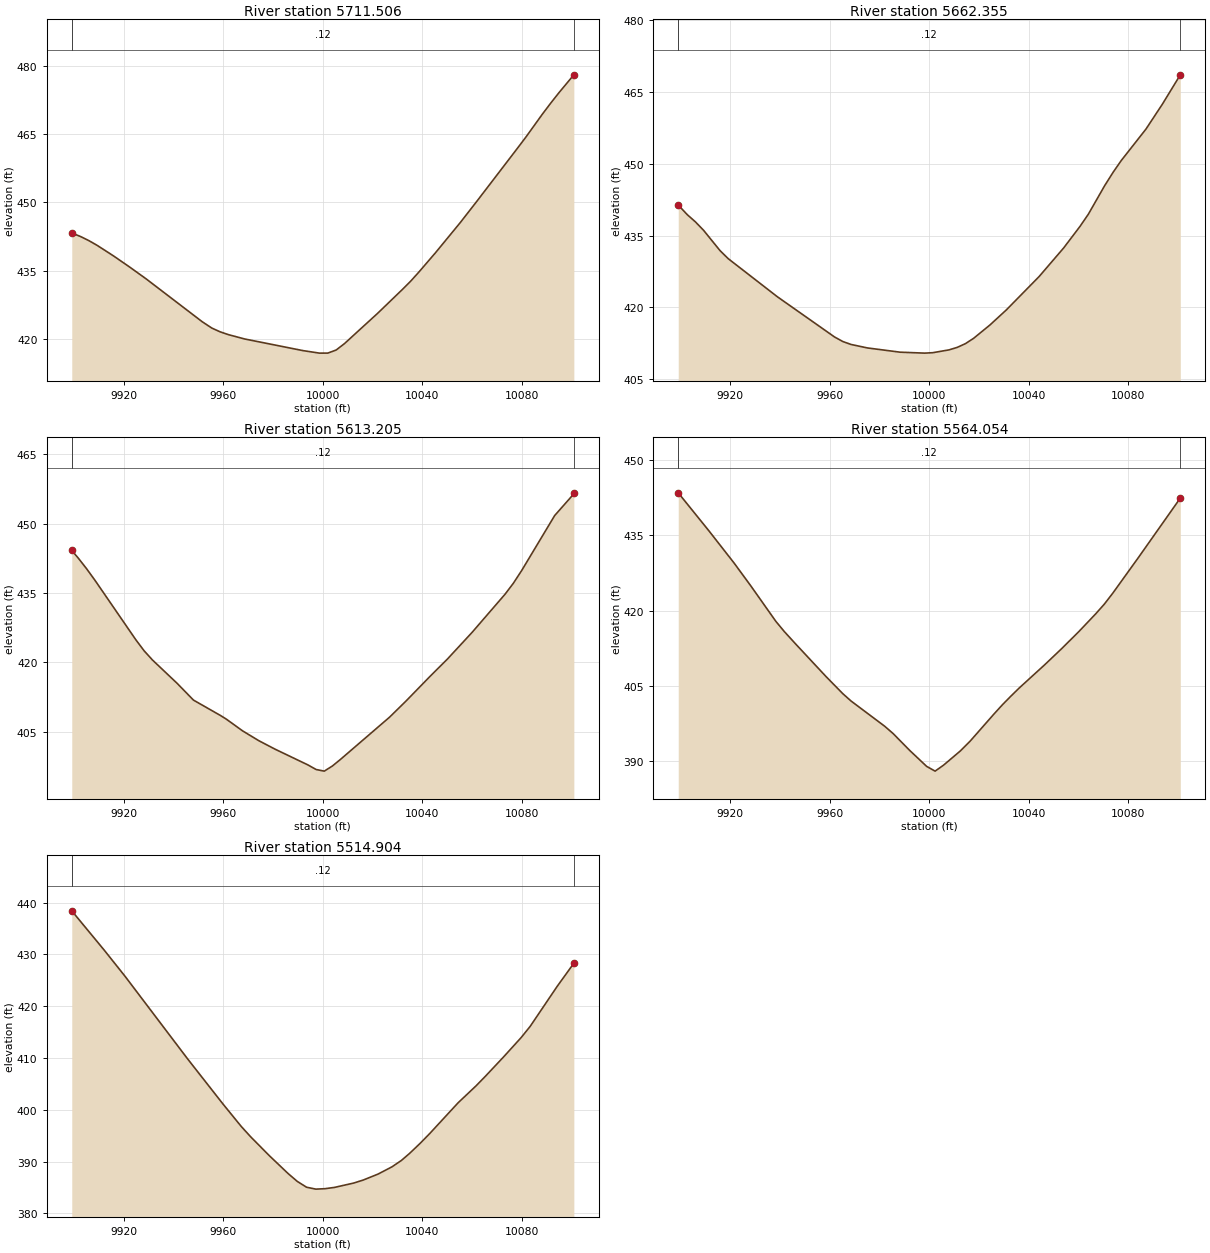
Type RM Length L Ch R = 1 ,5711.506,49.150500,49.150500,49.150500
XS GIS Cut Line= 6
1251435.66136189839165.9804251281251366.59181498839174.111313455
1251336.68271647839179.7622813371251334.73588215839180.220360063
1251304.86045963839186.058875843 1251235.9428506839195.407160847
#Sta/Elev= 30
9899.015443.30239902.534442.53469905.837441.64829909.141440.62329915.748438.3044
9922.355  435.829928.961433.23539951.536 423.8349955.389422.45149958.693421.6389
9961.996421.02499968.562420.07159991.976417.52379998.654416.968510002.01416.9749
10005.36417.6472 10008.7419.044610022.07425.701810032.09430.9633 10035.4432.7698
10038.71434.775210045.34438.980110055.27445.564610061.89450.200510078.44461.9778
10081.76464.376510088.38  469.3910091.69471.7751   10095474.059110100.99477.9791
#Mann= 3 , 0 , 0
9899.015    0.12       09899.015    0.12       010100.99    0.12       0
#XS Ineff= 2 , 0
       09972.537                       0
Bank Sta=9899.015,10100.99
Exp/Cntr=0.3,0.1

Type RM Length L Ch R = 1 ,5662.355,49.150500,49.150500,49.150500
XS GIS Cut Line= 6
1251429.19987616839123.1597899821251363.01082006839129.618119512
1251329.57231668839131.4715509471251327.57329253 839131.53402051
1251287.13567175839134.1095923561251228.16918549 839141.77142253
#Sta/Elev= 30
9899.007441.37859902.618439.37549905.915437.85649909.211436.08629915.804431.8543
  9919.1430.16529938.879422.19259961.954413.7552 9965.25412.81929968.537412.2121
9975.109411.48489988.252410.5972 9998.11410.399610001.39410.489910007.97411.0829
10011.26411.607710014.54412.385110017.83413.494410024.41416.290210030.98419.4305
10044.15426.400110054.07432.409310060.69436.9534   10064439.471410070.61445.4796
10073.92448.201310077.23450.692810087.16457.260210093.77462.474510100.98468.6129
#Mann= 3 , 0 , 0
9899.007    0.12       09899.007    0.12       010100.98    0.12       0
#XS Ineff= 2 , 0
       09969.616                       0
Bank Sta=9899.007,10100.98
Exp/Cntr=0.3,0.1

Type RM Length L Ch R = 1 ,5613.205,49.150500,49.150500,49.150500
XS GIS Cut Line= 6
1251428.28122952839073.3368097121251368.89726029839080.378841132
1251328.76149246839082.3390335061251326.76211717839082.389017947
1251286.31617884839084.7321123611251227.71960646839094.718793328
#Sta/Elev= 30
9899.016444.20769901.711442.49659905.015440.22069908.318437.76639924.838424.8281
9928.141 422.4619931.445420.50199941.357415.45479947.964411.80579958.816408.4764
9961.166407.68699967.735405.13749974.305402.99789980.874401.15599994.013397.7672
9997.298396.774510000.58396.424910003.87397.542910007.15398.988710026.87408.1225
10033.44411.591410043.33 417.05910049.98420.616710059.97426.428710073.28434.7225
10076.61437.084410079.94439.829410093.25451.7597 10099.9455.817510100.96456.6822
#Mann= 3 , 0 , 0
9899.016    0.12       09899.016    0.12       010100.96    0.12       0
#XS Ineff= 2 , 0
       0                               0
Bank Sta=9899.016,10100.96
Exp/Cntr=0.3,0.1

Type RM Length L Ch R = 1 ,5564.054,49.150500,49.150500,49.150500
XS GIS Cut Line= 5
1251421.18622905839010.4783426631251323.81883971839033.257740897
1251321.92147314839033.8901964851251289.41334653839041.949204763
1251225.66747033839060.882395744
#Sta/Elev= 30
9899.003443.52669911.312435.9529 9921.42429.52679928.159424.95719938.267417.8401
9941.637415.8178 9946.08 413.3979958.484406.78769965.223403.37219968.592401.8842
 9982.07396.86239985.439395.41049992.178392.00869998.917388.851210002.34387.8934
10005.72389.078710012.48391.923510016.45393.8948   10026399.291710029.38 401.139
10032.76402.844310036.16404.502210046.43409.152610053.28 412.38910060.12415.7624
10066.97419.345110070.39421.255310073.81423.455410084.08430.551710100.99442.4745
#Mann= 3 , 0 , 0
9899.003    0.12       09899.003    0.12       010100.99    0.12       0
#XS Ineff= 2 , 0
       0                               0
Bank Sta=9899.003,10100.99
Exp/Cntr=0.3,0.1

Type RM Length L Ch R = 1 ,5514.904,49.150600,49.150600,49.150600
XS GIS Cut Line= 6
1251399.64758027838943.9785906741251340.82422058838968.879054589
1251309.20877095838986.2773630151251307.47228467838987.269640888
1251265.51058233839012.6234209861251219.43456682839034.350673071
#Sta/Elev= 30
9899.037438.4008 9911.98430.87759920.396 425.8139945.665409.80739959.916401.0878
9967.252396.76519970.997394.79259978.487391.16059985.976387.73679989.721386.1952
9993.466385.06459997.211384.698310000.97384.784210004.81385.039810012.47385.8749
10016.31386.457810022.21387.598410027.81388.996410031.64390.2412 10034.9391.5882
 10039.3393.602410043.14395.490410054.39401.341410061.64404.628210065.27406.4133
10072.53410.114610079.78413.945510083.41416.106510094.29423.840910100.97428.2841
#Mann= 3 , 0 , 0
9899.037    0.12       09899.037    0.12       010100.97    0.12       0
#XS Ineff= 2 , 0
       0                               0
Bank Sta=9899.037,10100.97
Exp/Cntr=0.3,0.1