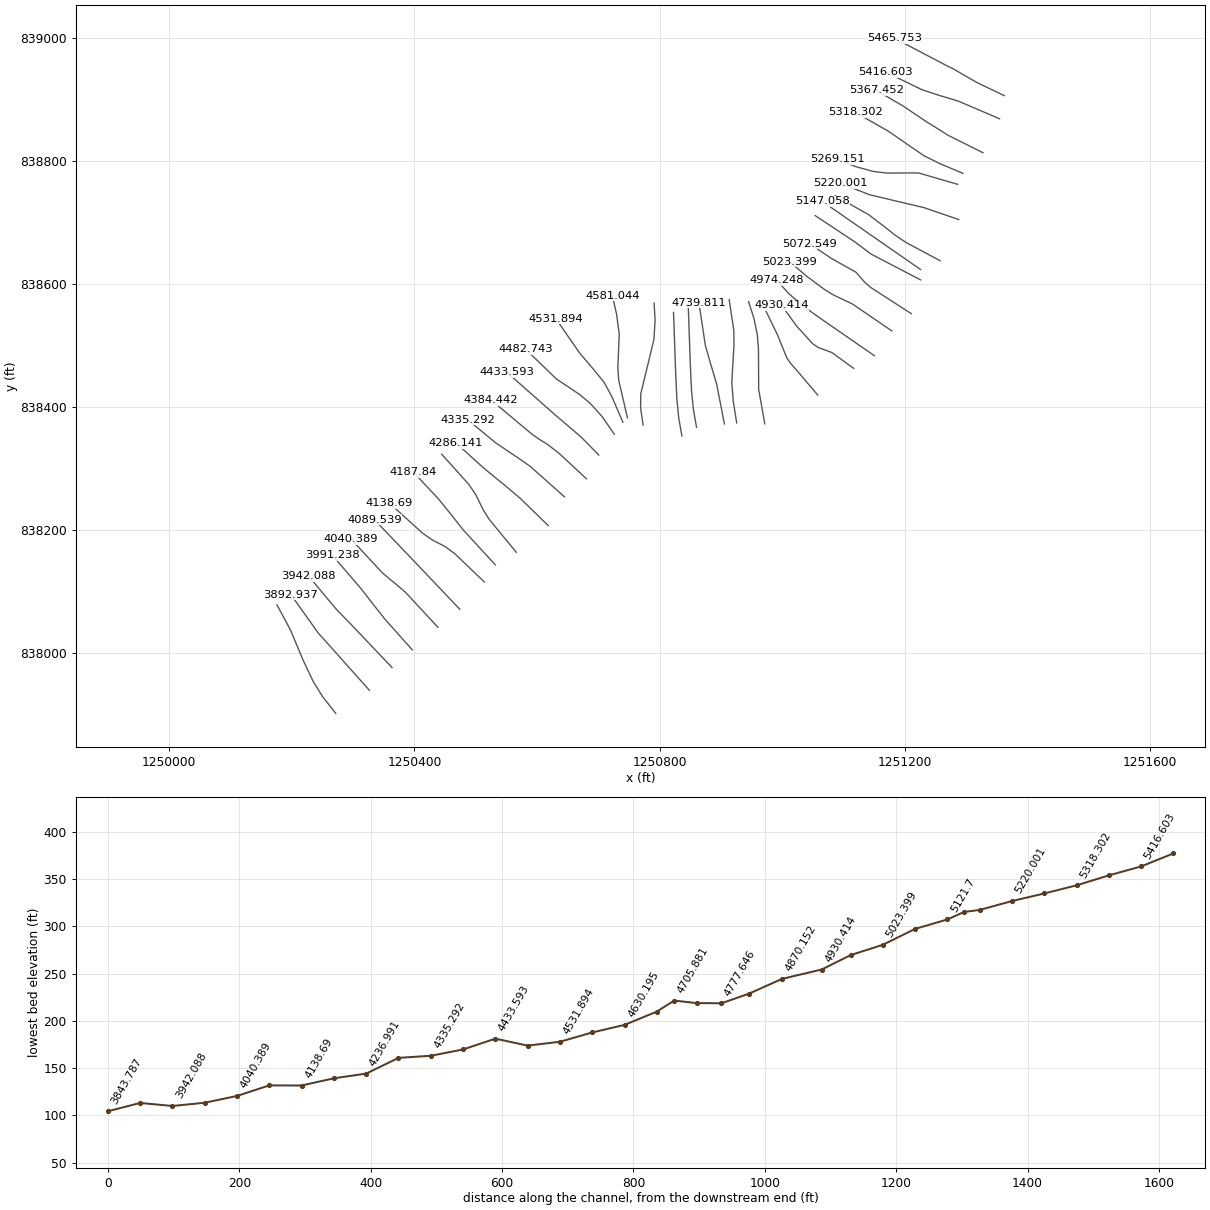
HEC-RAS study 77_ras.prj: 77

--- 77_ras.g01 (geometry) --- (continued)

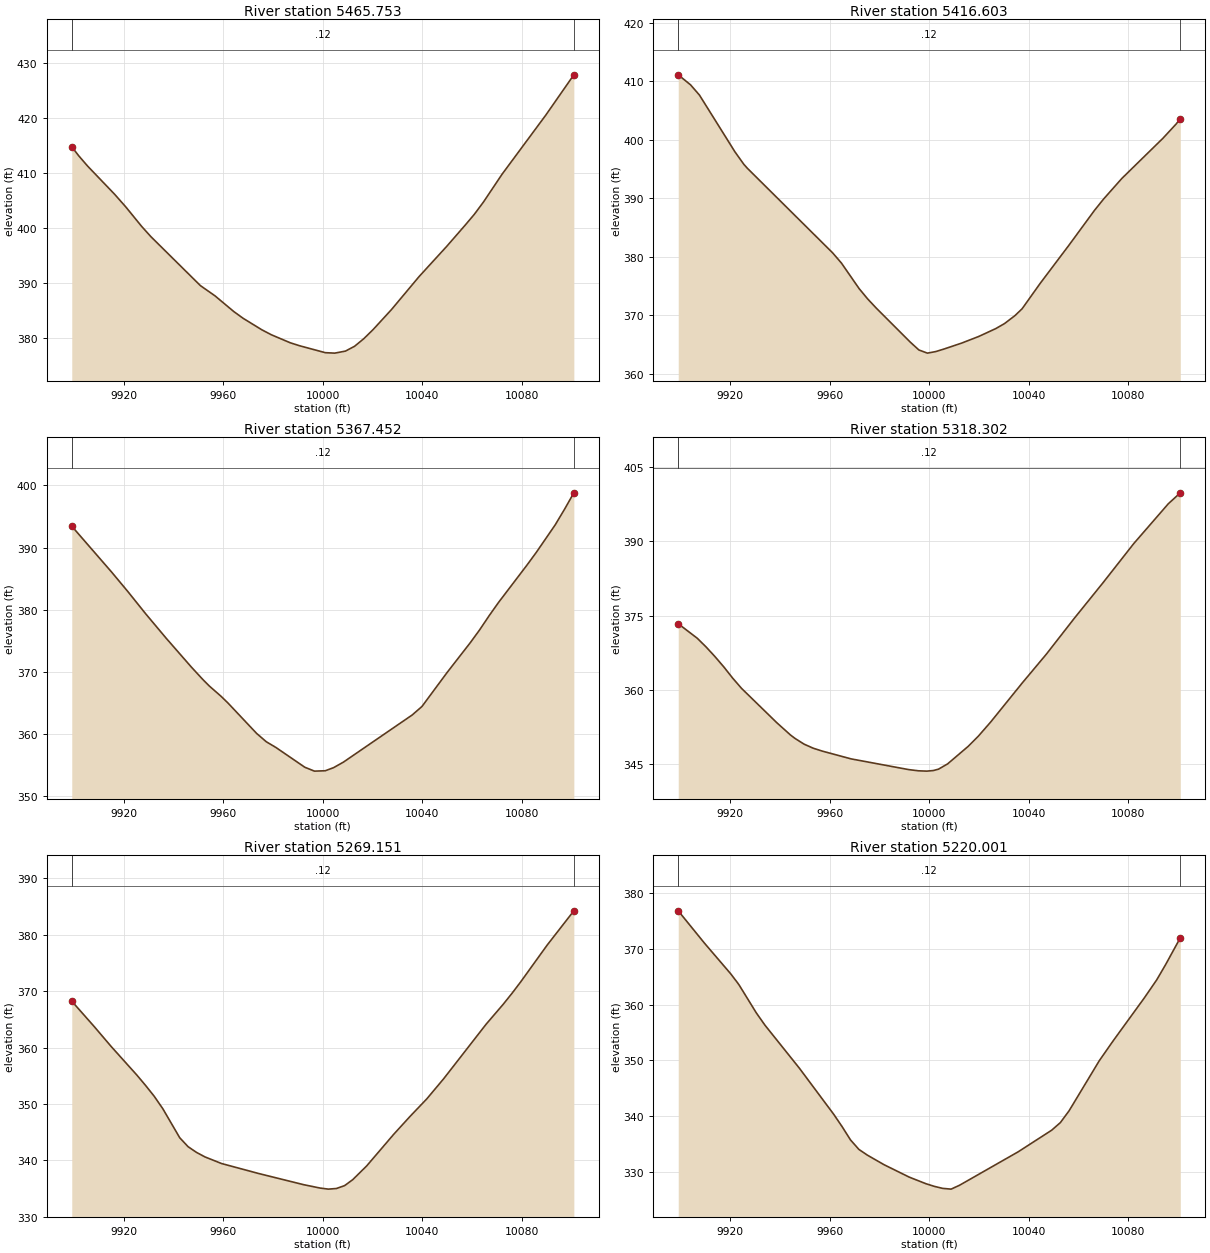
Type RM Length L Ch R = 1 ,5465.753,49.150500,49.150500,49.150500
XS GIS Cut Line= 6
1251362.44447632838906.8442476371251317.88659618838928.164488549
1251277.28123207838951.5239325941251273.90164341838953.121433762
1251272.02898505838953.8236806491251183.46956054839000.201316603
#Sta/Elev= 30
9899.021414.76999901.743413.1657 9905.38411.26189916.291406.11829920.733403.8435
9927.203400.2578 9930.84398.43539950.773389.5332 9956.62387.6837 9964.19384.8252
9967.975383.58759975.545381.4909 9979.33380.6006  9986.9379.15129990.685378.6056
   10001377.3509 10004.8377.269410009.11377.638410012.81378.523710016.52379.9078
10020.22381.543510027.63385.189810038.74391.187510049.85396.675810057.26400.5218
10060.96402.501310064.66404.751110072.07 409.75710089.66420.500510100.97 427.837
#Mann= 3 , 0 , 0
9899.021    0.12       09899.021    0.12       010100.97    0.12       0
#XS Ineff= 2 , 0
       0                               0
Bank Sta=9899.021,10100.97
Exp/Cntr=0.3,0.1

Type RM Length L Ch R = 1 ,5416.603,49.150500,49.150500,49.150500
XS GIS Cut Line= 6
1251354.70190325 838869.178405991251288.08298098838897.712725172
1251261.79110782838905.7498067061251259.82861018838906.135297311
1251228.04753344838916.5691240611251168.17931888 838945.48599825
#Sta/Elev= 30
9899.034411.0973 9903.99409.38589907.559407.63759921.836397.92739925.405395.7966
9926.841 395.1099961.096380.65549964.665378.89419971.792374.51699975.223372.7579
9978.653 371.1989992.376365.35739995.807364.02929999.232363.488910002.63363.7585
10006.08364.212610012.99365.201710019.89366.3393 10026.8367.699310030.25368.5448
10034.45369.907110037.31371.070710044.59375.422510056.27382.013210066.46387.9289
 10070.1 389.85210077.39 393.35310093.98400.254210099.25402.676810100.94403.5711
#Mann= 3 , 0 , 0
9899.034    0.12       09899.034    0.12       010100.94    0.12       0
#XS Ineff= 2 , 0
       0                               0
Bank Sta=9899.034,10100.94
Exp/Cntr=0.3,0.1

Type RM Length L Ch R = 1 ,5367.452,49.150500,49.150500,49.150500
XS GIS Cut Line= 6
1251327.56964584838813.9475726871251271.03918213838842.142130353
1251239.88773937838861.722643697 1251238.0827773838862.584102872
1251197.36450808838889.9021457871251153.40302044838915.669939475
#Sta/Elev= 30
9899.034393.45299914.996386.09979921.467382.99489928.799379.33879937.049 375.402
9947.131370.78489951.751368.78099954.463367.69479959.102 366.0729961.796365.0251
9973.398360.09939977.273358.76379981.148357.84169992.773354.65939996.648354.0343
   10001 354.09410004.33 354.58910008.28355.477210035.94363.061510039.89364.4342
10050.03369.917510059.28374.673410063.14 376.79110066.89379.027710070.69381.1751
 10082.1387.1701 10085.9 389.24410093.51393.674810097.31396.219910100.99398.8201
#Mann= 3 , 0 , 0
9899.034    0.12       09899.034    0.12       010100.99    0.12       0
#XS Ineff= 2 , 0
       0                               0
Bank Sta=9899.034,10100.99
Exp/Cntr=0.3,0.1

Type RM Length L Ch R = 1 ,5318.302,49.150500,49.150500,49.150500
XS GIS Cut Line= 6
1251294.85434961838780.4258482921251256.02497467838796.778783644
1251231.48564939838808.9831656181251206.33804491838826.110804255
1251174.78588107838848.0375546331251119.59123765838879.548426884
#Sta/Elev= 30
9899.035373.34559906.678370.40959910.238368.64239913.798366.69379917.357364.6065
9920.917362.33679924.477360.26449938.717353.28379944.147350.83029945.974350.1264
9949.638348.96339953.302348.14039956.966 347.5499968.574345.97289991.724343.8026
9995.694343.5566    9999343.494110001.61343.610310003.69343.884510007.37344.9544
10015.67348.514610019.66350.526410024.64 353.39910037.42361.357710047.06367.1552
10058.39374.473410069.72381.538210082.29389.598610096.17 397.64910100.98399.8552
#Mann= 3 , 0 , 0
9899.035    0.12       09899.035    0.12       010100.98    0.12       0
#XS Ineff= 2 , 0
       0                               0
Bank Sta=9899.035,10100.98
Exp/Cntr=0.3,0.1

Type RM Length L Ch R = 1 ,5269.151,49.150500,49.150500,49.150500
XS GIS Cut Line= 6
1251286.43719531838762.4634867871251222.33327635838781.068449931
1251170.68040079838780.7972195391251148.27205707838783.490295975
1251119.13688294838791.6114513611251090.85703233838803.005277122
#Sta/Elev= 30
9899.049368.23579907.976363.7833  9914.9360.1948 9925.28355.10289928.739353.2841
9932.199351.37149935.659349.1633 9942.46 344.0149945.826342.42689949.191341.4198
9952.557340.62399959.288339.43979974.105337.68069992.329335.68469998.902335.0919
 10002.2 334.90110005.48335.012410008.76335.524610012.04336.584110017.63339.0173
10028.53344.638410035.14347.831110041.79350.9003 10048.6354.484810065.63364.1339
10072.52367.678310076.06369.6263 10079.6371.683410090.21378.186810100.93384.2593
#Mann= 3 , 0 , 0
9899.049    0.12       09899.049    0.12       010100.93    0.12       0
#XS Ineff= 2 , 0
       0                               0
Bank Sta=9899.049,10100.93
Exp/Cntr=0.3,0.1

Type RM Length L Ch R = 1 ,5220.001,49.150500,49.150500,49.150500
XS GIS Cut Line= 6
1251288.01490179838705.1883477061251230.89044718838724.640343424
1251192.34014821838733.7865163611251190.37898688838734.178748689
1251142.69855388838745.5244781341251095.22560238838763.961550712
#Sta/Elev= 30
9899.034376.82439909.647370.98589920.045365.5659 9922.66364.03789923.511363.5145
9930.442358.49299933.908356.29399947.772348.55669961.574 340.2849964.946338.0652
9968.318335.68769971.689333.98549975.061332.96599981.805331.23819991.921329.0121
9998.665 327.82310002.02327.351510005.39326.987710008.77326.854710012.14327.5452
10035.75333.557210049.24337.443110052.72338.806510056.24340.939410068.38349.9263
10073.84353.4195 10086.5361.210310091.44364.420610094.96 367.11110100.94371.9811
#Mann= 3 , 0 , 0
9899.034    0.12       09899.034    0.12       010100.94    0.12       0
#XS Ineff= 2 , 0
       0                               0
Bank Sta=9899.034,10100.94
Exp/Cntr=0.3,0.1

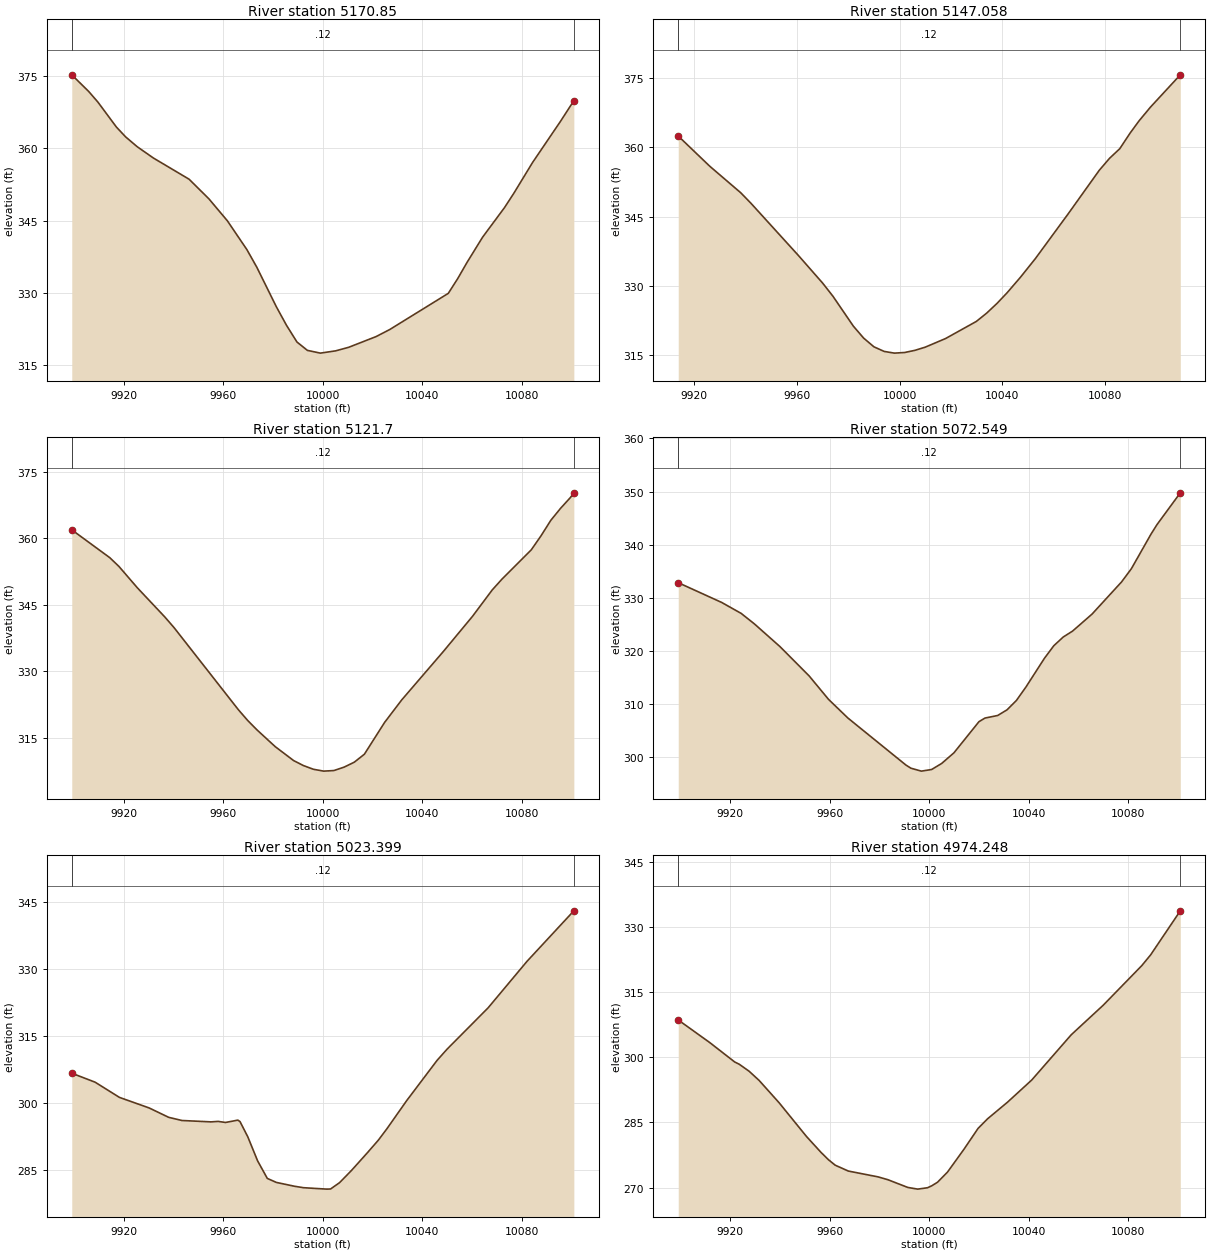
Type RM Length L Ch R = 1 , 5170.85,23.792300,23.792300,23.792300
XS GIS Cut Line= 6
1251257.71508938838638.0706550791251201.76499832838667.965317113
1251184.38710672838679.6048177091251172.18741763838689.362300783
1251141.35449679 838712.929293161251086.34358229838743.920151653
#Sta/Elev= 30
9899.027375.29349905.822 371.8459909.542 369.6289916.982364.44239920.701362.3974
9925.334360.36579931.861358.0099 9946.22353.60779954.179349.53439961.619344.9643
9969.465338.98039973.413335.36179981.311327.1121 9985.38323.27179989.581319.8004
9993.782 318.059    9999 317.48510005.19317.961210010.39318.694510021.39 320.914
10026.91322.386410050.46329.899610054.23332.951710057.99336.324810064.29341.5978
10073.05347.702610076.82350.693910084.34 357.07410095.65 365.68610100.95369.9192
#Mann= 3 , 0 , 0
9899.027    0.12       09899.027    0.12       010100.95    0.12       0
#XS Ineff= 2 , 0
       0                               0
Bank Sta=9899.027,10100.95
Exp/Cntr=0.3,0.1

Type RM Length L Ch R = 1 ,5147.058,25.358200,25.358200,25.358200
XS GIS Cut Line= 2
1251225.80699006838623.7880454511251065.00772598838735.069514841
#Sta/Elev= 30
9913.784362.48179926.077355.91919938.128350.16819942.117347.87869960.668336.4993
9970.046330.54089974.036327.70059982.016321.18969986.006318.60579989.996316.7215
9993.986  315.729997.976315.348810001.97315.484710005.96315.952910009.95316.6347
10017.92318.521810029.89 322.23110033.88 324.01710037.87326.105710041.86328.4461
10047.15 331.87810052.91335.8955 10065.8345.699510077.77 355.04810081.76357.6408
10085.75359.729910089.74363.089510093.27365.782310097.72368.767810109.33  375.77
#Mann= 3 , 0 , 0
9913.784    0.12       09913.784    0.12       010109.33    0.12       0
#XS Ineff= 2 , 0
       0                               0
Bank Sta=9913.784,10109.33
Exp/Cntr=0.3,0.1

Type RM Length L Ch R = 1 ,  5121.7,49.150500,49.150500,49.150500
XS GIS Cut Line= 6
1251225.89594594838606.842333915 1251145.8143348838648.519220143
1251137.92320429838654.1458358791251136.40012551838655.442073139
1251118.27189255838668.9034868931251053.72300377838711.632014833
#Sta/Elev= 30
9899.031361.8698  9914.3355.59479917.998353.61779925.396348.80059936.491 342.189
 9940.19339.7904 9966.08 321.2569969.778318.86449973.477316.75729980.874 312.945
9988.271 309.8049992.207308.67799996.237307.839610000.35 307.42210004.47307.5506
10008.56308.319310012.65309.430910016.73311.234610024.86318.405210031.79 323.514
10048.46334.391610060.27 342.38110068.14348.292110072.07350.738610083.87357.3551
10087.81360.540110091.74364.028410095.68366.740110099.61369.161510100.99370.2191
#Mann= 3 , 0 , 0
9899.031    0.12       09899.031    0.12       010100.99    0.12       0
#XS Ineff= 2 , 0
       0                               0
Bank Sta=9899.031,10100.99
Exp/Cntr=0.3,0.1

Type RM Length L Ch R = 1 ,5072.549,49.150500,49.150500,49.150500
XS GIS Cut Line= 6
 1251210.6561721838551.8798544041251144.99299056838594.203031081
1251134.81557266838602.9508130521251120.27459165 838619.47911682
 1251079.7545399838642.2039228591251045.11173003838665.554813927
#Sta/Elev= 30
9899.044332.86849916.543329.1434 9924.35  327.099929.625325.13389939.963320.8399
9951.673315.3328 9959.48310.91829967.286307.39719990.585298.56399992.617297.9602
9996.821297.411210000.94297.715710004.99298.857110009.91300.852810019.99306.7224
10022.41307.397310027.51307.881710031.28 308.94810035.04310.7077 10038.8313.1901
10046.32318.648810050.08321.007210053.85322.638710057.61323.757210065.44326.9507
10077.31333.005310081.27335.496610089.18 342.01810091.57 343.79410100.95 349.777
#Mann= 3 , 0 , 0
9899.044    0.12       09899.044    0.12       010100.95    0.12       0
#XS Ineff= 2 , 0
       09982.825                       0
Bank Sta=9899.044,10100.95
Exp/Cntr=0.3,0.1

Type RM Length L Ch R = 1 ,5023.399,49.150600,49.150600,49.150600
XS GIS Cut Line= 6
1251178.98615199838523.8012949591251114.58786053838567.650588006
1251083.42716742838582.471625873 1251069.2163858838591.172539163
1251039.62380906838613.1121119841251012.16063072838636.410154998
#Sta/Elev= 30
9899.043306.61389908.418304.60689918.215301.18789930.123298.82979938.061296.7051
9943.393 296.0019955.051295.69299957.907295.79879960.881295.56149965.845296.0868
 9966.71295.75619969.815292.37179973.784286.95039977.687 283.0079981.327 282.108
9988.607281.24889992.247280.922410001.61280.602310003.14280.637210006.76 282.061
10011.46284.743210018.01288.8122 10022.3291.562710025.71294.086110033.73300.4534
10045.98 309.50710050.06312.054210066.48 321.27810082.13331.718610100.97343.0555
#Mann= 3 , 0 , 0
9899.043    0.12       09899.043    0.12       010100.97    0.12       0
#XS Ineff= 2 , 0
       09973.519                       0
Bank Sta=9899.043,10100.97
Exp/Cntr=0.3,0.1

Type RM Length L Ch R = 1 ,4974.248,43.834600,43.834600,43.834600
XS GIS Cut Line= 6
1251150.53851629838483.3589125651251068.27492009838540.157152095
1251066.61081953838541.2665525381251033.78468429838564.538961221
1251010.46592495838585.0161431271250990.99404336838606.092297268
#Sta/Elev= 30
9899.033308.63719911.629303.46169921.756298.9465 9923.59 298.4239927.577296.8016
9931.564294.69749939.538 289.5989950.628281.76839956.402278.13979959.472276.4034
9962.176275.15169967.446273.80189979.406272.45949983.393271.79929991.367 270.024
9995.354269.63449999.337269.9595   10001270.404310003.33271.226210007.35273.5748
10013.96278.833110019.63283.635210023.43285.838710031.48289.684610041.24294.8066
10057.11305.227910069.94312.026310085.45 321.15210089.03323.645810100.97333.8016
#Mann= 3 , 0 , 0
9899.033    0.12       09899.033    0.12       010100.97    0.12       0
#XS Ineff= 2 , 0
       09972.639                       0
Bank Sta=9899.033,10100.97
Exp/Cntr=0.3,0.1

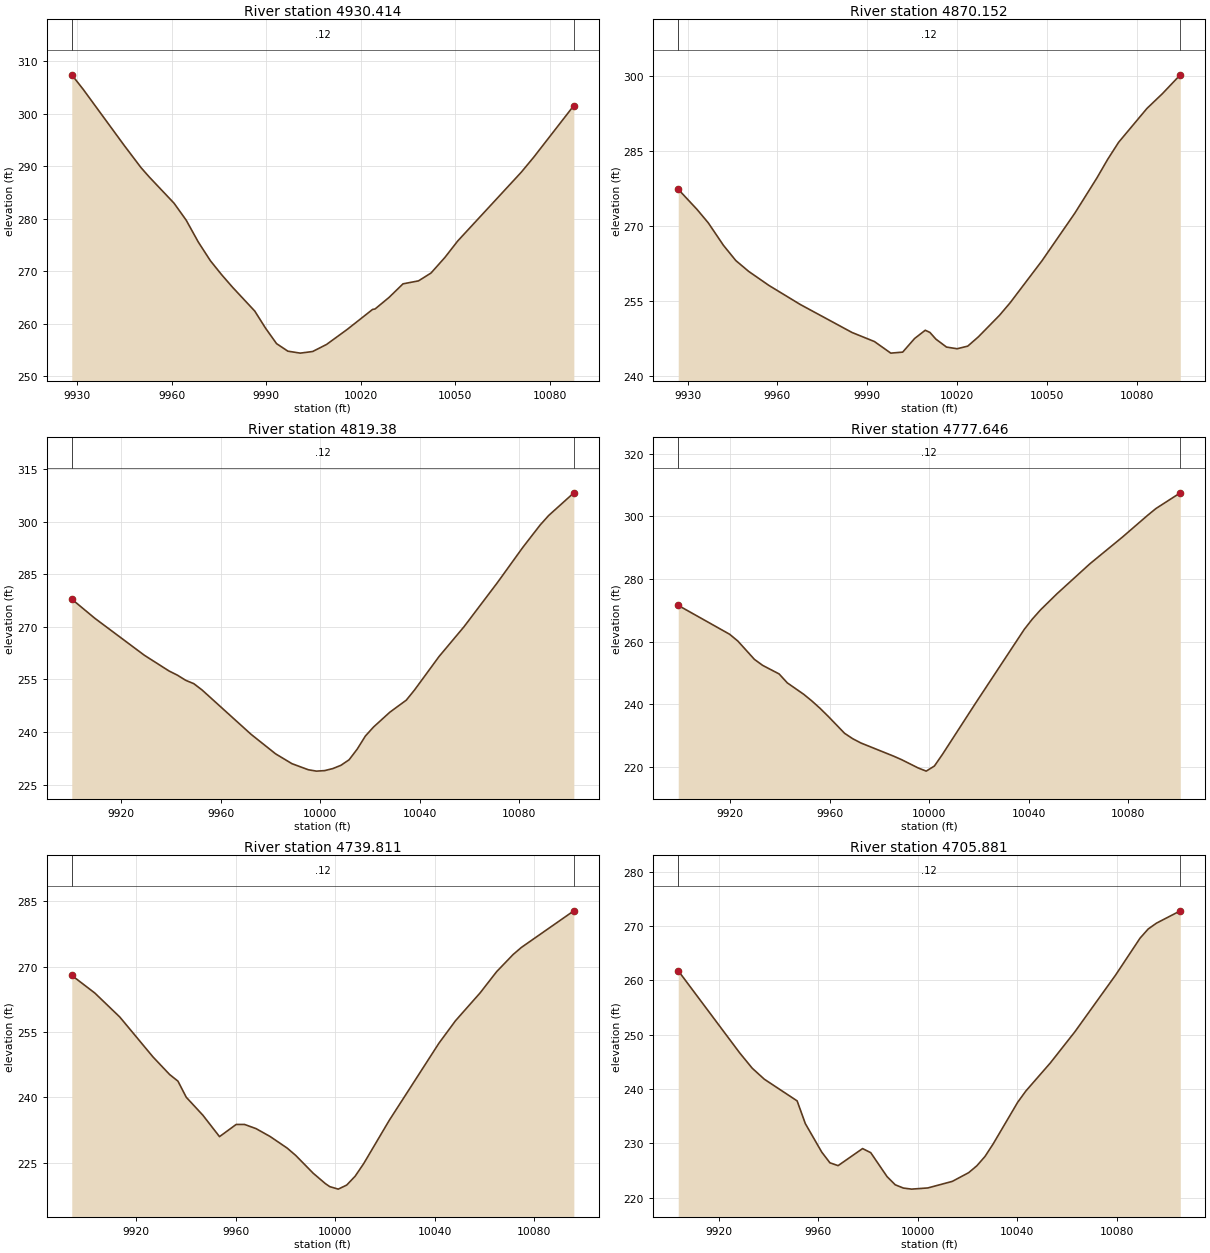
Type RM Length L Ch R = 1 ,4930.414,60.262000,60.262000,60.262000
XS GIS Cut Line= 6
1251116.73012352838462.8387797771251081.04581356 838488.62090537
1251059.02154696838496.732229233 1251049.9910357838502.743091971
1251022.97875419838532.3331133431250999.12408397838565.654819131
#Sta/Elev= 30
9928.231307.39439931.824304.66269944.962293.90549950.208289.75449952.848287.9565
9960.725282.96919964.569279.75449968.412275.59789972.256 272.0379975.796269.3972
9979.329266.96559986.366262.44689989.791259.19679993.278256.25689996.885254.8171
10000.83254.446410004.77254.756910009.18256.099910015.69258.936910023.78262.7545
10024.58262.847110029.02265.043310033.46267.627910038.38268.192710042.35269.6828
10046.75 272.63710050.82275.768110070.99288.839510075.03291.754110087.73301.5487
#Mann= 3 , 0 , 0
9928.231    0.12       09928.231    0.12       010087.73    0.12       0
#XS Ineff= 2 , 0
       09983.388                       0
Bank Sta=9928.231,10087.73
Exp/Cntr=0.3,0.1

Type RM Length L Ch R = 1 ,4870.152,50.772000,50.772000,50.772000
XS GIS Cut Line= 6
1251058.09894952838419.3039372861251023.37672728838460.102548376
1251013.96184844838470.6059339941251007.49914634838480.043697178
1250991.96447027838518.3306400781250971.22641727838560.696561605
#Sta/Elev= 30
9926.875277.31359933.161273.28449936.917270.59359941.979266.10829946.085263.0805
9950.394260.90469957.166258.09599967.626254.28939984.923248.69039992.368246.8899
9997.827244.5742 10001.8 244.77610005.78247.497610009.34249.146510010.89248.7093
10012.88247.374510016.43245.784510019.97245.449710023.51245.967910027.05247.8163
10034.13 252.13810037.67254.633210048.32263.044910059.28272.551110066.59279.5334
10070.24283.302410073.89286.706110083.33293.4626 10088.5296.418610094.48300.1864
#Mann= 3 , 0 , 0
9926.875    0.12       09926.875    0.12       010094.48    0.12       0
#XS Ineff= 2 , 0
       09975.472                       0
Bank Sta=9926.875,10094.48
Exp/Cntr=0.3,0.1

Type RM Length L Ch R = 1 , 4819.38,41.733400,41.733400,41.733400
XS GIS Cut Line= 6
1250971.61455487838372.5616245621250961.67258762838428.516641846
1250961.30977503838494.3715499941250959.36973993838518.061384414
1250953.83806677838544.692320253 1250945.1531358838571.516389812
#Sta/Elev= 30
9900.092277.8751 9909.43272.38019929.326261.8513 9939.26257.36399942.572256.1946
9945.883254.73579949.195253.75729952.507251.95849972.235239.29989982.079233.7465
9988.641230.94829995.204229.21839998.485228.822710001.77228.970510005.05229.5447
10008.33 230.48110011.61232.054410014.89235.105110018.17238.832710021.45241.4051
10028.03 245.64210034.62249.067310037.91251.946210047.81261.528910057.86270.0322
10071.26282.586510081.53292.689610088.43299.004210091.88301.7338   10102308.2001
#Mann= 3 , 0 , 0
9900.092    0.12       09900.092    0.12       0   10102    0.12       0
#XS Ineff= 2 , 0
       09973.812                       0
Bank Sta=9900.092,10102
Exp/Cntr=0.3,0.1

Type RM Length L Ch R = 1 ,4777.646,37.835400,37.835400,37.835400
XS GIS Cut Line= 6
1250925.76851645838374.1340932871250920.13994518838409.700698102
1250917.82333987838440.0916293961250921.35472886838500.604278735
1250921.11987878838524.4682750651250913.55393405 838574.79627164
#Sta/Elev= 30
9899.045271.59399919.728262.3732 9923.05 260.1929929.693254.35389933.015252.4417
9939.615249.71639942.905246.86919949.486243.23289952.776   241.19956.067238.7557
9959.357236.18729965.937230.77579969.221229.04049972.504227.6789 9985.64223.4854
9988.924222.33859995.491219.72859998.775218.696510002.07 220.32610005.36224.1062
10018.52240.250710038.23 263.95910041.51267.273710044.79270.190110051.36275.2963
10064.55284.8293 10077.8 293.46410087.82300.336910091.16302.499510100.97 307.519
#Mann= 3 , 0 , 0
9899.045    0.12       09899.045    0.12       010100.97    0.12       0
#XS Ineff= 2 , 0
       0 9976.61                       0
Bank Sta=9899.045,10100.97
Exp/Cntr=0.3,0.1

Type RM Length L Ch R = 1 ,4739.811,33.929400,33.929400,33.929400
XS GIS Cut Line= 6
1250905.76472074838372.3270934581250893.00521583838437.629803058
1250883.44607501 838469.67541027 1250882.8260338838471.576869948
 1250874.5608199838500.8628670981250864.18267772838569.622066962
#Sta/Elev= 30
9894.086267.96249903.371263.90769913.399258.41269926.771249.24069933.457245.2058
9936.799243.68879940.142239.99069946.828235.86519953.514230.9544  9960.2233.7464
9963.613 233.7479968.234232.78589973.884230.97919980.732228.31979984.155226.6466
9991.189222.55739996.064220.18319997.858219.480310001.27218.906310004.68219.8401
10008.08221.883610011.49224.752910021.72234.634310041.76 252.39310048.39 257.528
10058.35263.961510064.98268.822910071.62272.761210074.94274.384310096.03282.7831
#Mann= 3 , 0 , 0
9894.086    0.12       09894.086    0.12       010096.03    0.12       0
#XS Ineff= 2 , 0
       09978.301        10011.76       0
Bank Sta=9894.086,10096.03
Exp/Cntr=0.3,0.1

Type RM Length L Ch R = 1 ,4705.881,26.536200,26.536200,26.536200
XS GIS Cut Line= 6
1250860.24841056 838366.948467071250855.15797998838396.249378771
 1250852.0940741838426.6873012411250850.25489133838466.298981744
1250850.17495525838468.2973836611250846.63363355838568.213269674
#Sta/Elev= 30
9903.696261.79069928.395246.67849933.436243.85589938.336241.81619951.526237.8267
9954.823233.64399961.418 228.4069964.713226.43199967.997225.9081 9977.85229.0494
9981.135228.29399987.703223.88419990.988222.38229994.272221.78029997.557221.5835
10004.13221.803210013.97223.014110020.54224.616810023.82225.883810027.11227.6047
10030.39229.919210040.24237.570910043.52239.642310053.37 244.81410063.22250.5346
10079.63260.994710089.48267.796110092.76 269.48210096.05270.545610105.66272.8203
#Mann= 3 , 0 , 0
9903.696    0.12       09903.696    0.12       010105.66    0.12       0
#XS Ineff= 2 , 0
       0 9983.76        10020.36       0
Bank Sta=9903.696,10105.66
Exp/Cntr=0.3,0.1

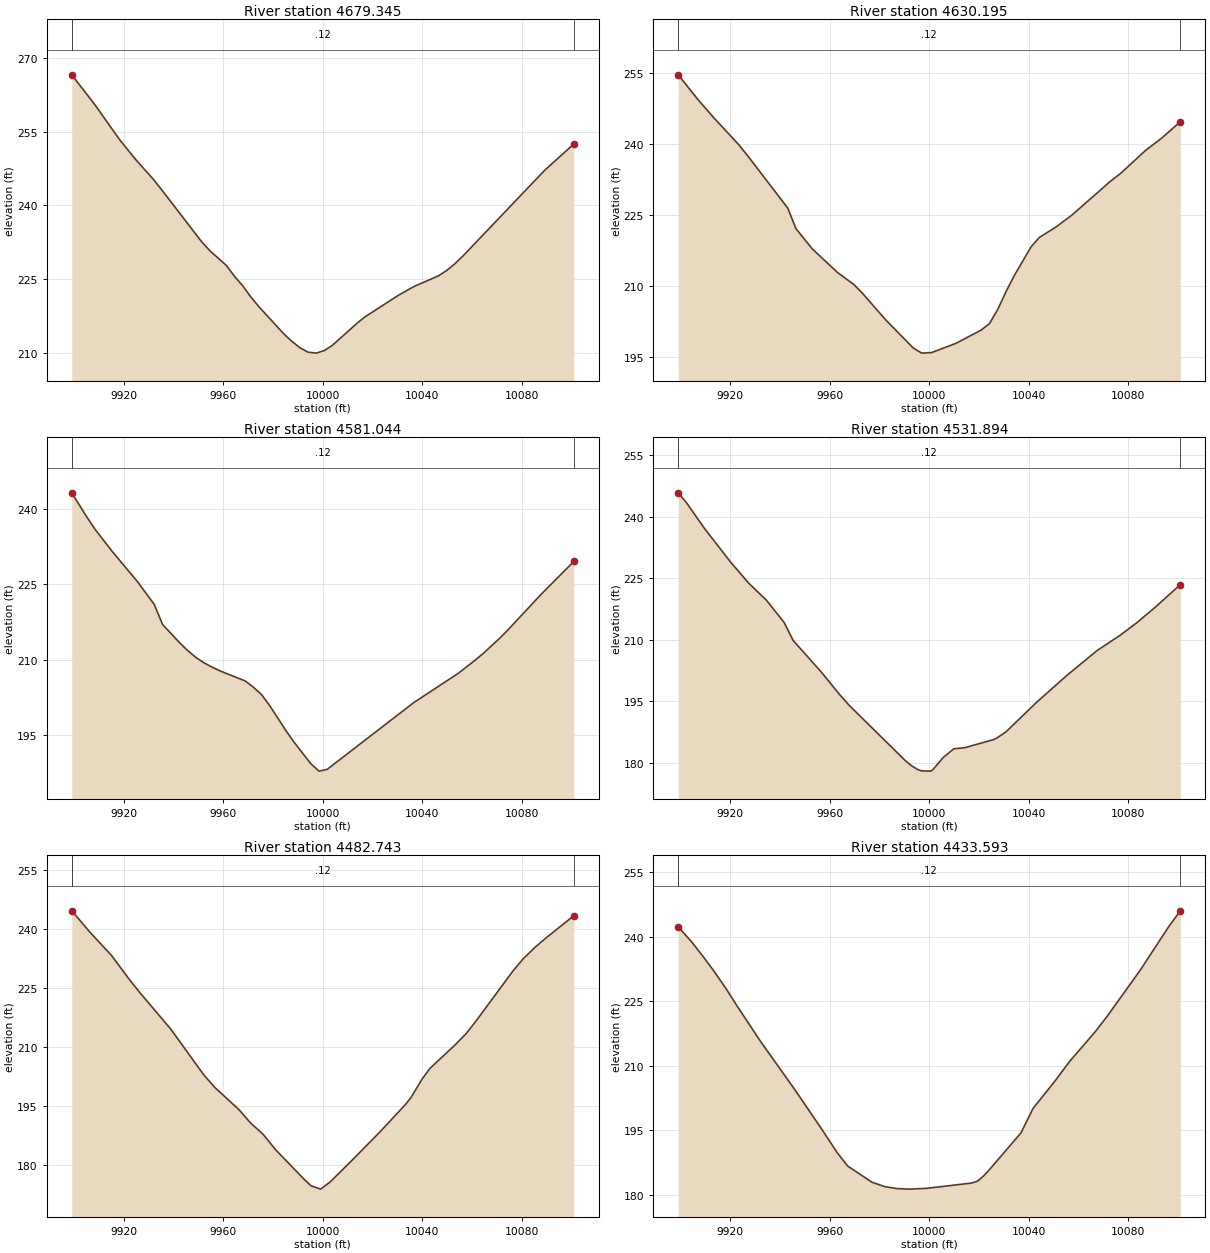
Type RM Length L Ch R = 1 ,4679.345,49.150500,49.150500,49.150500
XS GIS Cut Line= 6
1250836.37688278838352.625550403 1250831.2864522838381.926462105
1250828.22254633838412.3643845751250826.38336355838451.976065077
1250826.30342748838453.9744669951250822.76210578838553.890353007
#Sta/Elev= 30
9899.014266.5917 9908.28260.5245 9918.27253.3809 9924.93249.21619931.562245.4656
 9934.86243.39149951.347232.53079954.644 230.7259961.232227.74939964.516225.5261
  9967.8223.60539971.085221.31919974.369219.31719984.222213.87589987.507212.3243
9990.791211.00099994.075210.0971 9997.36209.904410000.64210.441810003.93211.5228
10013.78215.999510017.06217.318310030.19221.618810036.76223.4929 10046.6225.6639
10049.89226.761310053.17228.129610056.45229.732710089.28247.164310100.98252.5045
#Mann= 3 , 0 , 0
9899.014    0.12       09899.014    0.12       010100.98    0.12       0
#XS Ineff= 2 , 0
       09990.738        10032.62       0
Bank Sta=9899.014,10100.98
Exp/Cntr=0.3,0.1

Type RM Length L Ch R = 1 ,4630.195,49.150500,49.150500,49.150500
XS GIS Cut Line= 6
1250773.10557932838370.4814405811250769.03779158838398.366039284
1250769.24444628838421.1012018551250790.75328696838509.929919042
1250792.66460975838540.9757742471250791.03431667838569.259916066
#Sta/Elev= 30
9899.072254.71459906.831249.58539913.462245.58339923.409239.94599927.252237.4154
9943.135226.50639946.416222.1689 9953.02217.86899963.001212.95469969.656210.3666
 9973.03208.57449982.607202.82119993.562196.93839996.984 195.845   10001195.9696
10010.67197.898210020.87200.719510024.22202.086410027.57205.110110030.92 208.898
10034.26212.318310040.96218.334910044.26220.322610050.83222.480410057.41225.0663
10072.62232.091510077.13 233.95110086.99238.726410093.56241.366410100.95244.8021
#Mann= 3 , 0 , 0
9899.072    0.12       09899.072    0.12       010100.95    0.12       0
#XS Ineff= 2 , 0
       09978.442        10030.32       0
Bank Sta=9899.072,10100.95
Exp/Cntr=0.3,0.1

Type RM Length L Ch R = 1 ,4581.044,49.150500,49.150500,49.150500
XS GIS Cut Line= 6
1250747.59005558838382.2733013721250733.27041997838443.706549957
1250731.88179794838464.8589393151250734.22149836838517.973057812
1250729.86531031838551.0831828061250722.94466177 838581.24337687
#Sta/Elev= 30
9899.047243.21439904.987238.49859908.389235.96799915.193231.62899925.399225.5842
9932.203221.0316 9935.57217.01569942.241213.49169945.577211.86759948.913210.4844
9952.248209.38439955.584208.5031 9958.92207.72739968.831205.77559972.118204.5333
9975.406203.04869978.694 200.8389985.273195.83679988.565 193.5199995.151189.3408
9998.444187.840110001.74188.184610036.62201.491510054.44207.284210061.06209.8362
10064.37211.1865   10071214.213910074.37 215.89610087.83223.031910100.96229.5697
#Mann= 3 , 0 , 0
9899.047    0.12       09899.047    0.12       010100.96    0.12       0
#XS Ineff= 2 , 0
       09975.474                       0
Bank Sta=9899.047,10100.96
Exp/Cntr=0.3,0.1

Type RM Length L Ch R = 1 ,4531.894,49.150600,49.150600,49.150600
XS GIS Cut Line= 6
1250740.17278267838375.1229514341250721.85238359838417.377784632
1250709.23944936838440.3882907271250691.75814681838461.792281374
1250669.56487568838487.7796346011250630.96758843838543.510374238
#Sta/Elev= 30
9899.068 245.8299902.378243.42359909.529237.23089920.257228.85529927.409223.8122
9934.561219.64739941.713214.18859945.296209.84019956.521202.21339964.003196.6422
9967.745194.08119990.302180.62249992.682179.40959995.488 178.3569996.918 178.076
10000.54178.010510001.29178.248910005.59181.309110009.89183.4532 10014.2183.7044
10025.87185.6909 10027.1186.029510030.94187.6259 10043.5194.967710055.48 201.399
10067.45207.368110076.73211.101310083.41214.139710091.39218.210510100.97223.4619
#Mann= 3 , 0 , 0
9899.068    0.12       09899.068    0.12       010100.97    0.12       0
#XS Ineff= 2 , 0
       09963.683                       0
Bank Sta=9899.068,10100.97
Exp/Cntr=0.3,0.1

Type RM Length L Ch R = 1 ,4482.743,49.150500,49.150500,49.150500
XS GIS Cut Line= 6
1250726.06723314838355.6453034361250706.32161034838384.197679313
1250687.35192484838405.3389136561250670.06404371838419.923912073
1250631.55751023838445.6610869491250581.32461399838494.084830874
#Sta/Elev= 30
9899.066244.64869906.495239.13999915.103233.27719922.451227.01869926.439223.8802
9938.892214.58469952.116203.00519956.524199.80449966.392194.06379970.914 190.776
9976.002187.8606 9981.09183.90329992.664176.32999995.292174.76879999.157173.9225
10002.96175.7412 10011.6181.131710022.62188.215310033.26 195.42910035.48197.1955
10039.91201.847510043.04204.556710052.81 210.33110057.61 213.39710062.03216.9738
10076.44229.326210080.68232.501810085.36235.372510090.04 237.89510100.98243.4033
#Mann= 3 , 0 , 0
9899.066    0.12       09899.066    0.12       010100.98    0.12       0
#XS Ineff= 2 , 0
       0                               0
Bank Sta=9899.066,10100.98
Exp/Cntr=0.3,0.1

Type RM Length L Ch R = 1 ,4433.593,49.150500,49.150500,49.150500
XS GIS Cut Line= 5
1250700.78924889838321.7254740051250672.29502119838350.702064496
1250627.15699853838389.1894125511250625.70699971838390.566911518
1250550.63247746838456.599805786
#Sta/Elev= 30
9899.042242.32059904.568238.74219909.169235.32599913.433231.98919918.112228.0861
9922.973223.67989932.176215.64029945.676204.65049956.717195.27419962.923189.8213
 9966.83186.90459967.234186.64249976.943182.8956    9982181.88319987.056181.3944
9992.113181.2791    9999181.467810016.99182.688510019.31183.101410021.95184.3923
10023.68185.467510036.86194.347610041.82200.125710049.89205.935910056.73211.1928
10066.66217.841110071.63221.563910084.85232.229410096.47 242.50110100.98246.0564
#Mann= 3 , 0 , 0
9899.042    0.12       09899.042    0.12       010100.98    0.12       0
#XS Ineff= 2 , 0
       0                               0
Bank Sta=9899.042,10100.98
Exp/Cntr=0.3,0.1

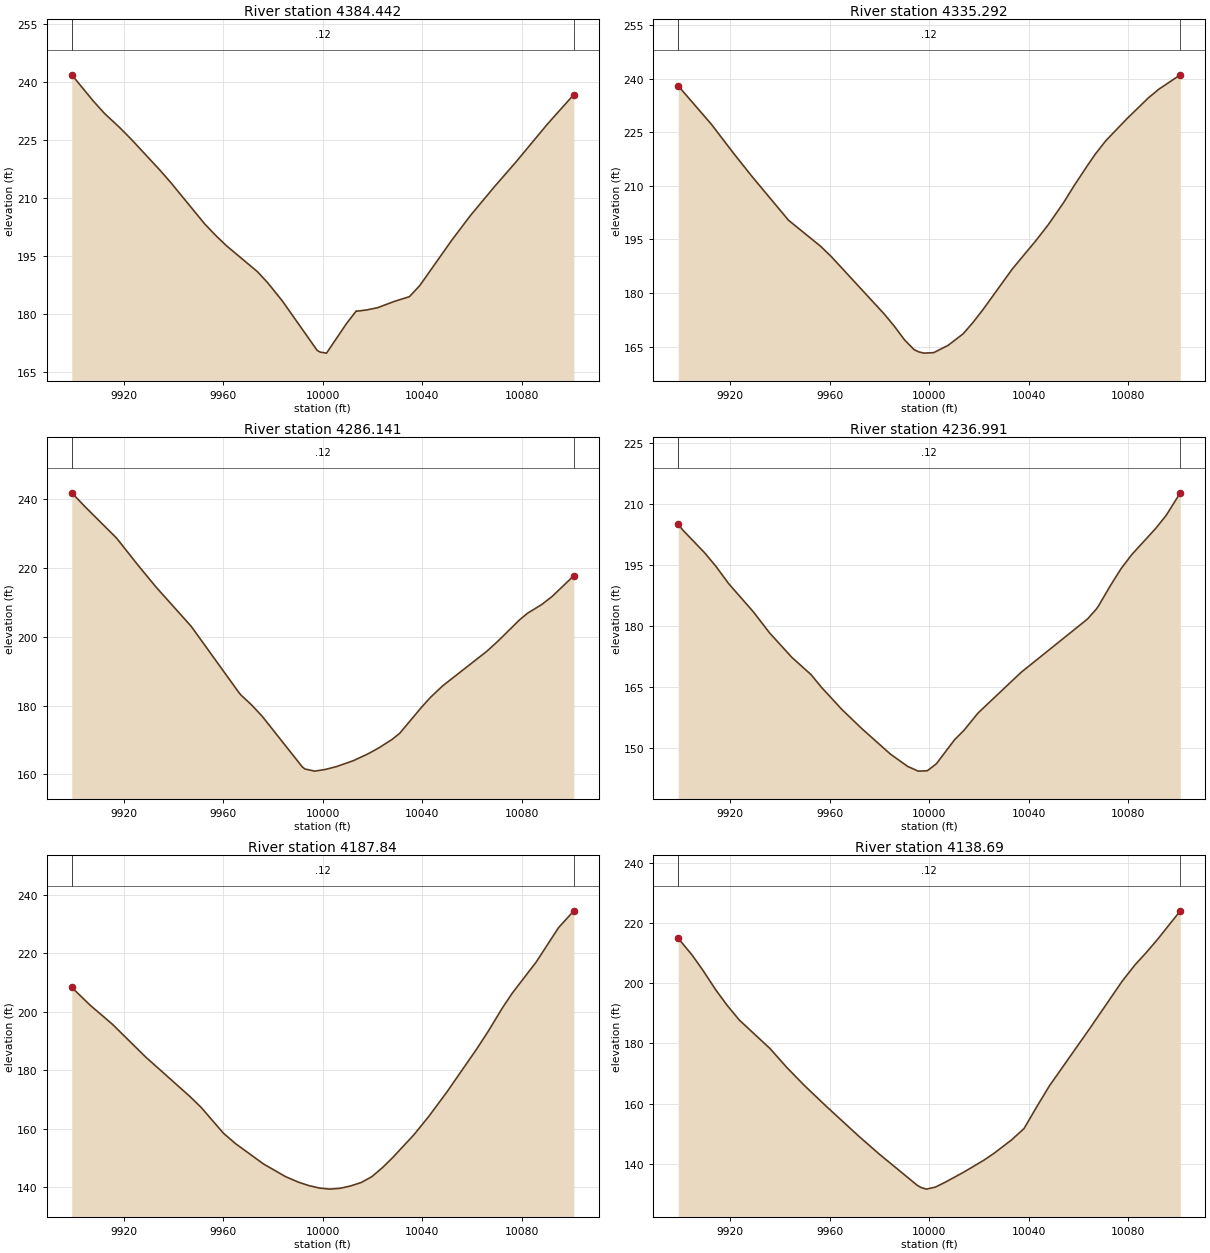
Type RM Length L Ch R = 1 ,4384.442,49.150500,49.150500,49.150500
XS GIS Cut Line= 6
1250680.63621198838283.0516354641250636.20154936838324.351347988
1250617.07089872838339.0779875821250602.54353156838348.141942851
1250591.95420046838355.5170890521250525.14219495838411.372384678
#Sta/Elev= 30
9899.047241.76669907.705235.00349912.184231.8093 9918.27228.17239923.089225.0499
 9934.58217.08249939.059213.79499952.496203.26289956.975200.24549961.323 197.574
9973.744 190.9019977.884 188.0299983.854183.2492 9997.78170.5439    9999170.1188
10001.52169.863510009.52177.480710013.51180.7879 10013.9180.702210017.76181.0341
10022.04181.599510028.75183.214310034.87184.457710038.98187.290110051.97199.1091
10059.44 205.45310069.08212.885110077.63219.188310090.46229.109310100.99236.6741
#Mann= 3 , 0 , 0
9899.047    0.12       09899.047    0.12       010100.99    0.12       0
#XS Ineff= 2 , 0
       0                               0
Bank Sta=9899.047,10100.99
Exp/Cntr=0.3,0.1

Type RM Length L Ch R = 1 ,4335.292,49.150500,49.150500,49.150500
XS GIS Cut Line= 6
1250644.92888162838253.5569354161250588.99919922 838303.24103105
1250568.40229605838317.6604497981250566.69573238838318.703349818
1250533.13056906838341.1701114531250487.13538851838379.031046561
#Sta/Elev= 30
9899.047238.01439912.428 227.2369921.205219.23469928.582212.76759943.402200.3884
9956.312193.0937  9960.7190.13359981.875174.1397 9985.88170.76819990.076166.8575
9993.889164.14799995.797163.50489997.894163.1637 10001.8163.300310007.62165.3551
10013.65168.5931 10017.6171.770410021.54175.301610033.39186.724610042.81194.6204
10047.97199.243210054.02205.319110058.27210.092610063.46215.555410066.77218.9123
10071.02222.685410079.52228.845610088.02234.604110092.27237.070510100.96241.1252
#Mann= 3 , 0 , 0
9899.047    0.12       09899.047    0.12       010100.96    0.12       0
#XS Ineff= 2 , 0
       0                               0
Bank Sta=9899.047,10100.96
Exp/Cntr=0.3,0.1

Type RM Length L Ch R = 1 ,4286.141,49.150500,49.150500,49.150500
XS GIS Cut Line= 6
1250618.30998047838206.8520438381250572.90907113838250.983714129
1250544.87654261 838274.614401061250543.27654265838275.814401107
 1250511.9303276838301.4957180471250467.84144815838341.404731126
#Sta/Elev= 30
9899.021 241.8979904.737237.58159917.029228.7427 9926.18220.39339932.979214.4409
  9947.1203.03969966.221183.84069967.046183.10659971.337180.22329975.628176.9063
9991.673162.25769992.792161.58089996.763160.9524   10001161.434910005.52162.2732
10012.36 164.01410018.24165.992510022.72167.786610027.89170.181710030.97171.9749
10039.45179.308610043.32182.408310048.21185.747610065.91195.762810070.34198.6732
10079.19204.982910082.43206.907910088.04209.390110092.21 211.72710100.99217.7968
#Mann= 3 , 0 , 0
9899.021    0.12       09899.021    0.12       010100.99    0.12       0
#XS Ineff= 2 , 0
       0                               0
Bank Sta=9899.021,10100.99
Exp/Cntr=0.3,0.1

Type RM Length L Ch R = 1 ,4236.991,49.150500,49.150500,49.150500
XS GIS Cut Line= 6
1250566.20659806838163.4299435531250521.98693312 838217.05969419
 1250512.0360026838232.8928472591250500.33745871838256.823021351
1250488.81090355 838273.857474891250444.37256185838323.278273374
#Sta/Elev= 30
9899.024 205.0229900.977203.54549909.668198.01239914.309194.60249919.313190.4376
 9929.32183.44269935.739178.34089944.696172.31449952.462168.04179956.594164.9593
9964.859159.4783 9972.84154.78229984.465 148.451 9991.35145.4565 9995.57144.3099
9999.212144.401610002.84146.104310010.17152.0328 10013.9154.311410019.63158.6159
10036.86168.5728 10063.6181.712510067.18184.171610068.12185.000210072.63189.7288
10077.15194.134610081.49197.614510091.04203.999410095.22207.178910100.97212.7803
#Mann= 3 , 0 , 0
9899.024    0.12       09899.024    0.12       010100.97    0.12       0
#XS Ineff= 2 , 0
       0                               0
Bank Sta=9899.024,10100.97
Exp/Cntr=0.3,0.1

Type RM Length L Ch R = 1 , 4187.84,49.150500,49.150500,49.150500
XS GIS Cut Line= 6
1250531.96862292838143.0292265331250479.68924293838199.726363263
1250465.51217528838217.6677922151250464.34356588838219.290860933
1250438.83338786838250.7545715391250398.08593529838294.069234045
#Sta/Elev= 30
9899.012208.39799906.455202.2579 9915.38195.76319928.768 184.5389946.619170.9909
9951.082167.29489960.007158.49479964.925154.88859976.133147.96489985.045143.5998
9990.337141.68029994.475140.53379998.657 139.70910002.79139.343610007.01139.6357
10011.23140.445810015.46141.618910019.68143.588710023.91146.640210028.13150.1683
10036.58157.894910042.61164.221810049.76172.411810061.77187.147110066.55193.3891
10072.28201.428110076.13206.3375 10085.8217.034810094.81228.829810100.97234.5963
#Mann= 3 , 0 , 0
9899.012    0.12       09899.012    0.12       010100.97    0.12       0
#XS Ineff= 2 , 0
       0                               0
Bank Sta=9899.012,10100.97
Exp/Cntr=0.3,0.1

Type RM Length L Ch R = 1 , 4138.69,49.150500,49.150500,49.150500
XS GIS Cut Line= 6
1250514.04618402838115.1219434661250465.78493306838161.118913792
   1250450.36819838172.5051377731250428.96816005838183.600861777
1250412.92587889838194.8661338871250359.25879614 838243.35218326
#Sta/Elev= 30
9899.062  214.899904.644209.32829908.834204.46959914.155197.78579918.911192.4703
9923.666187.74879936.028178.28249942.687172.09089949.625 166.2119958.689159.1006
 9971.63 149.2939979.787143.40379995.125133.00879996.582132.28629998.848131.7039
10002.47132.368510006.15133.870410013.92137.350510021.94141.278610025.95143.5166
10033.04147.976610038.14151.812310043.24159.011710048.34165.954810064.65185.0952
10077.59200.659910082.76206.086310087.11210.002810091.88214.589410100.97223.9995
#Mann= 3 , 0 , 0
9899.062    0.12       09899.062    0.12       010100.97    0.12       0
#XS Ineff= 2 , 0
       0                               0
Bank Sta=9899.062,10100.97
Exp/Cntr=0.3,0.1

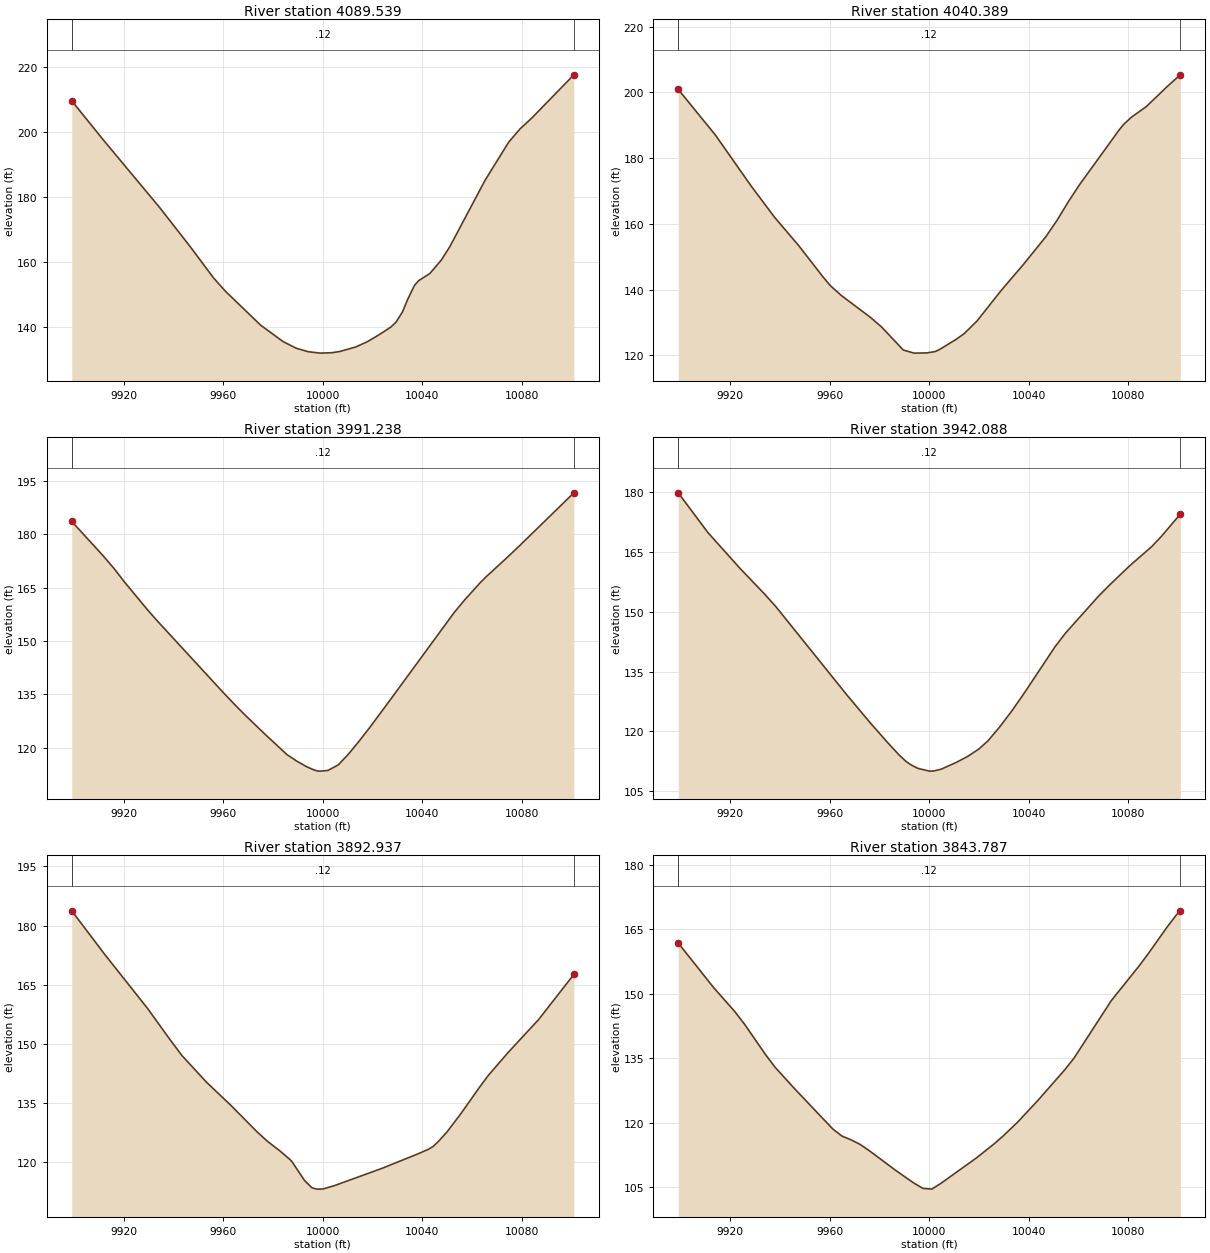
Type RM Length L Ch R = 1 ,4089.539,49.150500,49.150500,49.150500
XS GIS Cut Line= 4
 1250474.1662827838070.5346469681250405.15539883838142.904132998
 1250403.8068601838144.3811039831250334.62838576838216.582942068
#Sta/Elev= 30
9899.001209.53649911.532197.64829934.199176.82939946.545164.73629956.053154.9895
9960.807150.9091    9975140.44359984.066135.36819989.331133.34019994.085132.2897
    9999 131.84210003.63131.964910006.71132.328110013.12133.707710017.86135.3302
 10022.6137.473610027.34 139.85510029.42141.344710032.09144.585910033.97148.1002
10036.83152.653910038.51154.126910043.06156.3605 10047.6160.430610051.06164.5764
10065.28185.075510074.86196.9001 10079.4200.935910083.95204.142710100.99217.5428
#Mann= 3 , 0 , 0
9899.001    0.12       09899.001    0.12       010100.99    0.12       0
#XS Ineff= 2 , 0
       0                               0
Bank Sta=9899.001,10100.99
Exp/Cntr=0.3,0.1

Type RM Length L Ch R = 1 ,4040.389,49.150600,49.150600,49.150600
XS GIS Cut Line= 6
1250438.32723542 838041.275525341250385.82801524838097.883001502
1250368.57367878838112.7136272521250366.89132183838113.795142435
  1250347.677741838129.9871213551250296.68139482838184.748217137
#Sta/Elev= 30
9899.043200.93089913.889 187.1549928.363171.54389937.893161.92729947.662153.2462
9957.312143.82319960.266141.17749964.741138.15089976.248131.61719980.899128.5749
9989.552121.61459993.878120.6757    9999120.7417 10002.3121.139910003.94 121.682
10010.88124.899510014.13 126.66410019.22130.465510029.01139.835510037.91147.6975
10046.94156.163410051.42161.116810055.91166.721310060.39171.890210076.42188.6628
10078.32190.391310081.23192.431610087.29195.708910095.68 201.80610100.96205.3726
#Mann= 3 , 0 , 0
9899.043    0.12       09899.043    0.12       010100.96    0.12       0
#XS Ineff= 2 , 0
       0                               0
Bank Sta=9899.043,10100.96
Exp/Cntr=0.3,0.1

Type RM Length L Ch R = 1 ,3991.238,49.150500,49.150500,49.150500
XS GIS Cut Line= 6
1250396.44375245838004.6288526121250352.14181839 838054.22706791
 1250331.3181684838080.4504471851250330.13544112838082.063257213
1250313.09198112  838103.86884991250265.98360172838158.739306406
#Sta/Elev= 29
9899.011183.52749911.559173.95829915.958170.38089920.242166.52679929.155159.0194
9933.554155.52759959.948 135.5459964.347 132.3199968.592129.31539976.971123.6982
9985.602118.12489989.539116.28939993.729114.66099996.154113.92059997.918113.5195
    9999113.496410002.04113.683810006.21115.228910010.37118.314310014.53121.8352
 10018.7125.568710027.03133.392410052.91158.037110057.23161.649510063.45166.4405
10065.88168.119610074.53173.664710078.85176.516810100.99191.5563
#Mann= 3 , 0 , 0
9899.011    0.12       09899.011    0.12       010100.99    0.12       0
#XS Ineff= 2 , 0
       0                               0
Bank Sta=9899.011,10100.99
Exp/Cntr=0.3,0.1

Type RM Length L Ch R = 1 ,3942.088,49.150500,49.150500,49.150500
XS GIS Cut Line= 5
1250363.40742694837975.8122251691250294.49414397838048.254405338
1250293.03203348838049.6190418841250271.83669404838071.471234758
1250227.28038774838124.858970104
#Sta/Elev= 30
9899.015179.8915 9910.95169.92049923.965160.86129933.485 154.6549938.245151.3609
9966.806129.19579976.326122.10339983.401117.09839987.929114.05349990.606112.4943
9992.458111.68729995.366110.740610000.06110.035410001.64110.053910004.73110.5065
10010.78112.195610015.35113.692610019.92115.568810023.58117.616410028.29121.0999
10033.14125.085510038.26129.670510050.58141.246810054.85144.715410067.67153.6705
10071.95156.404710080.49161.504710089.46166.385310093.31  168.9210100.98174.5437
#Mann= 3 , 0 , 0
9899.015    0.12       09899.015    0.12       010100.98    0.12       0
#XS Ineff= 2 , 0
       0                               0
Bank Sta=9899.015,10100.98
Exp/Cntr=0.3,0.1

Type RM Length L Ch R = 1 ,3892.937,49.150500,49.150500,49.150500
XS GIS Cut Line= 5
1250326.56453019837938.655654587  1250259.954783838013.223856409
1250258.56856561838014.6655225811250243.27150166838031.666927841
1250198.52224602838094.448846833
#Sta/Elev= 30
9899.014183.72669912.039172.88029929.636158.89559938.469151.16529943.394147.0344
9953.244140.30439963.093134.41839973.628127.70319977.867125.28819982.792122.8989
9986.825120.73089987.717120.08349992.642115.43249995.624113.59499997.567113.2474
    9999113.246910000.06113.2921 10004.5114.091210023.87 118.52410038.42122.2151
10042.45123.328410044.35124.050510046.48125.305410050.01127.778510055.66132.4654
10062.59138.662610066.62142.085410074.68 147.95210086.77156.163910100.97 167.617
#Mann= 3 , 0 , 0
9899.014    0.12       09899.014    0.12       010100.97    0.12       0
#XS Ineff= 2 , 0
       0                               0
Bank Sta=9899.014,10100.97
Exp/Cntr=0.3,0.1

Type RM Length L Ch R = 1 ,3843.787,49.150500,49.150500,49.150500
XS GIS Cut Line= 6
1250271.65555896837901.089342325  1250250.147106837928.430057042
1250235.14727062837952.5231246011250218.51103783837987.561756568
1250197.79093218838036.8936003071250175.81375223838077.832153193
#Sta/Elev= 30
9899.044161.83329913.283151.4452 9921.73145.90799925.806142.84549934.131135.8603
9937.996132.89129945.725127.96079961.184118.51979964.875116.86169968.504115.9952
9972.133114.92989975.762113.50599986.648108.79739994.059105.81369997.534104.6554
   10001104.496410004.75105.867310018.99111.7655 10026.1115.050810029.66116.8504
10035.54120.0989 10043.9125.299610054.51132.3007 10058.3135.080910073.19148.3942
10084.36156.471810088.09159.348210095.53165.449110099.26168.289210100.97169.3327
#Mann= 3 , 0 , 0
9899.044    0.12       09899.044    0.12       010100.97    0.12       0
#XS Ineff= 2 , 0
       0                               0
Bank Sta=9899.044,10100.97
Exp/Cntr=0.3,0.1