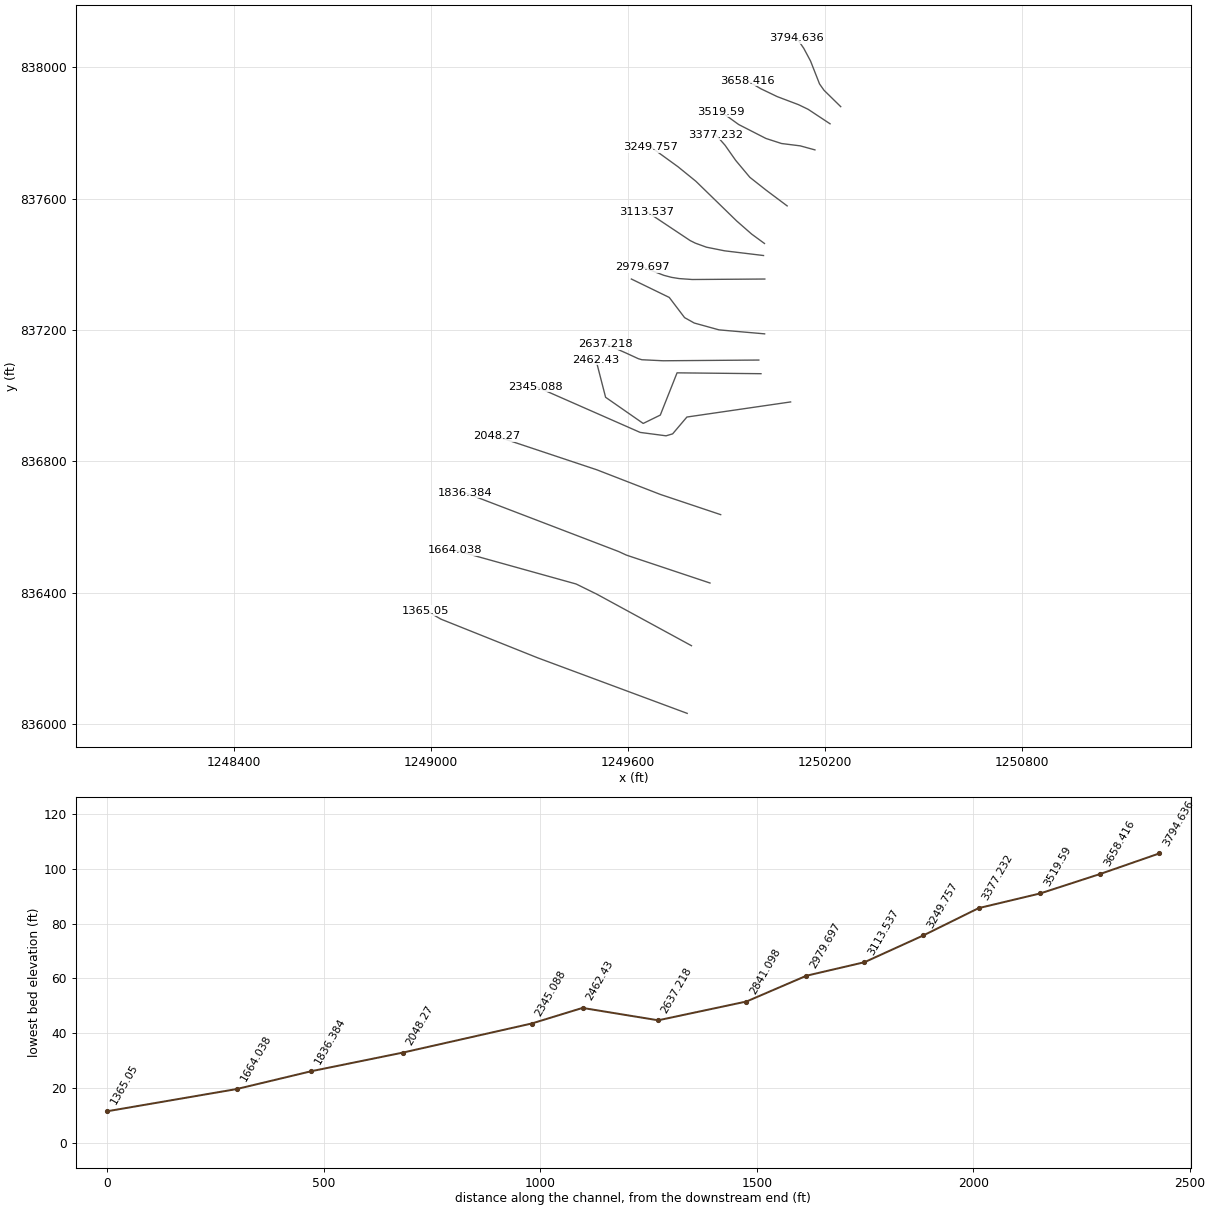
HEC-RAS study 77_ras.prj: 77

--- 77_ras.g01 (geometry) --- (continued)

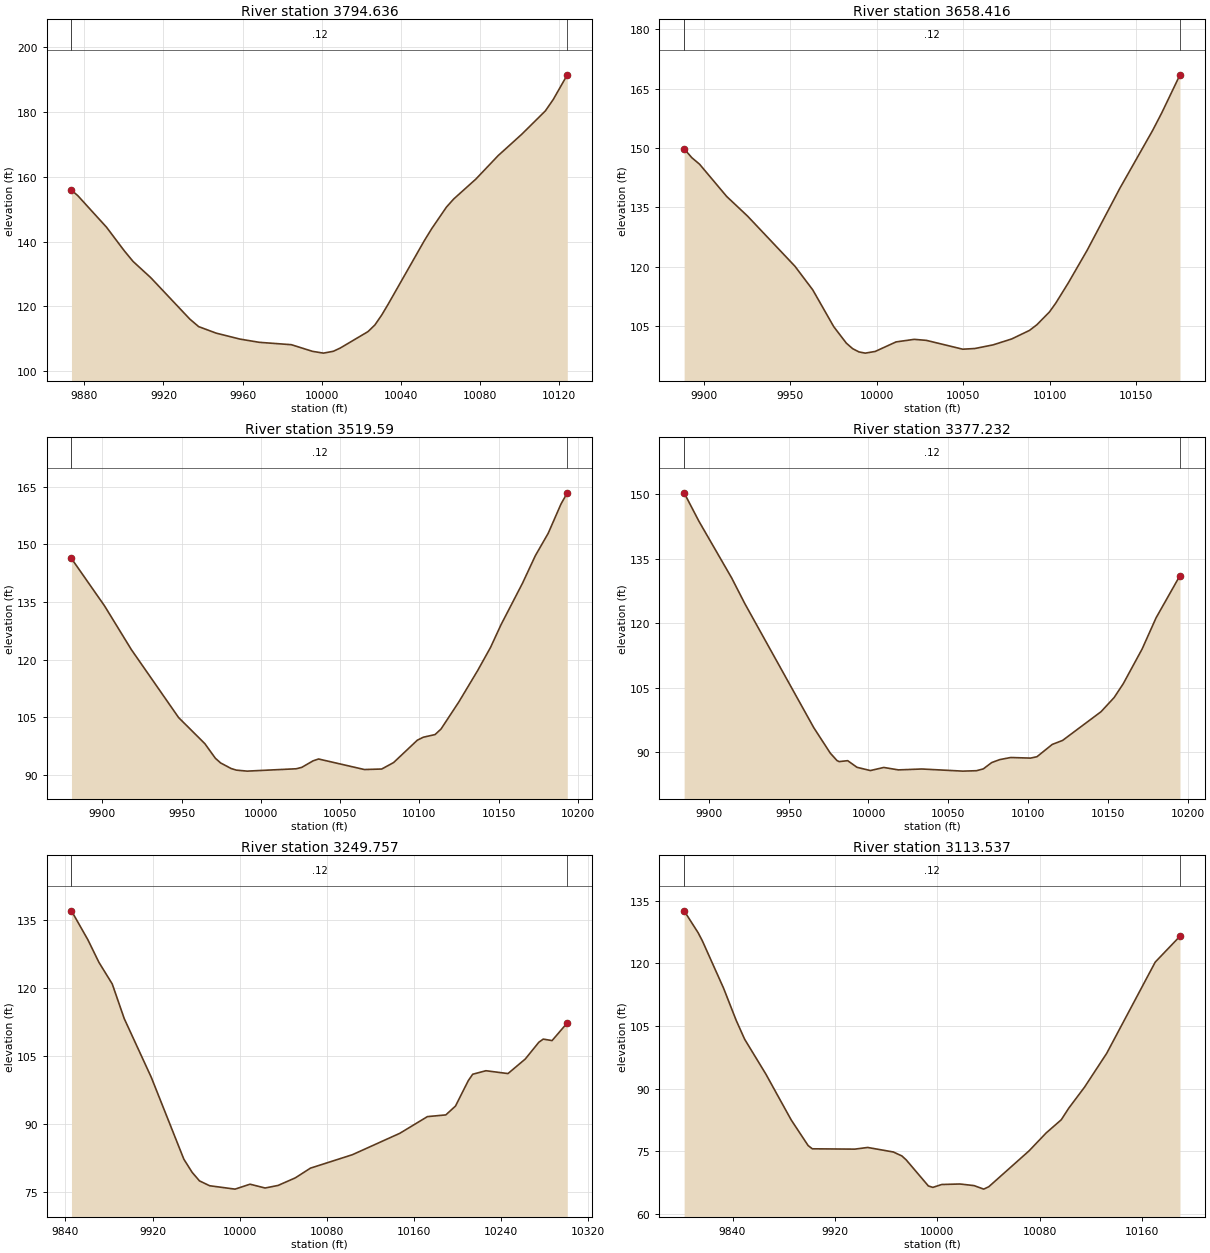
Type RM Length L Ch R = 1 ,3794.636,136.219800,136.219800,136.219800
XS GIS Cut Line= 6
1250247.77419212837880.6058287321250196.74336064837930.697642133
1250183.22724897837949.8698709611250155.82207087838019.659900129
1250135.13063547838058.398946479 1250114.2977868838088.756037846
#Sta/Elev= 30
9873.481155.91599876.659154.23839891.224144.4655 9900.17137.20579904.621133.9109
9913.567   128.99933.292116.12089937.787113.77349946.592111.76699958.634109.9219
9968.498108.91639984.685108.18339995.375106.129810000.91105.579910005.94106.1557
10009.44107.162210023.44112.222310026.94114.288910030.44117.407110033.78120.8416
10051.94140.332710055.66144.0224 10063.1150.678110066.82153.212910077.98159.3318
10089.26166.587910101.19173.179410113.13 180.39610117.11183.916110124.23191.5399
#Mann= 3 , 0 , 0
9873.481    0.12       09873.481    0.12       010124.23    0.12       0
#XS Ineff= 2 , 0
       0                               0
Bank Sta=9873.481,10124.23
Exp/Cntr=0.3,0.1

Type RM Length L Ch R = 1 ,3658.416,138.826300,138.826300,138.826300
XS GIS Cut Line= 6
 1250215.3265242837828.3474734431250148.40334934837872.559258595
1250119.24727756837886.6381333021250054.17053059837911.237409666
1250003.99559486837935.3814127891249961.89802754837960.245932753
#Sta/Elev= 30
9888.483149.7937 9892.94147.55399897.427145.90089913.089137.75049925.178132.7762
9952.562120.09929962.883114.1112 9975.01104.80919982.302100.63069985.94899.23793
9989.59498.41394 9993.2498.10534    999998.5299710011.06100.943810021.58101.5903
10028.59101.335110049.6499.1003310056.65 99.270410067.17100.191710077.96101.6928
10088.27 103.85910092.53105.290910099.81108.527710103.45110.754610110.73115.8957
10121.65124.164910140.48139.781310159.54154.498410164.86158.986510175.31168.5274
#Mann= 3 , 0 , 0
9888.483    0.12       09888.483    0.12       010175.31    0.12       0
#XS Ineff= 2 , 0
       0                               0
Bank Sta=9888.483,10175.31
Exp/Cntr=0.3,0.1

Type RM Length L Ch R = 1 , 3519.59,142.357700,142.357700,142.357700
XS GIS Cut Line= 6
1250169.19071418837748.8981554511250124.58625016837761.141368926
1250067.32731467837768.3452141731250019.86319673837783.743063375
1249936.92947811837826.1425182971249883.67765322837864.558566898
#Sta/Elev= 30
 9880.54  146.289901.456133.93249918.329 122.5939948.154104.91529964.71298.12789
9971.33494.339489974.64693.119969981.26991.67135 9984.5891.250839991.37990.98927
 10022.4 91.6027 10025.991.9755310032.8993.6431810036.4594.1449710065.3791.40284
10076.3191.5364410083.7993.2149710098.7599.0267610102.4999.7976210109.97 100.499
10113.71101.930610124.93108.961610136.84117.145510144.93123.1319 10151.6129.0801
10165.16139.872810173.25147.025610181.34 152.82510189.43160.4567 10193.4163.3553
#Mann= 3 , 0 , 0
 9880.54    0.12       0 9880.54    0.12       0 10193.4    0.12       0
#XS Ineff= 2 , 0
       0                10076.85       0
Bank Sta=9880.54,10193.4
Exp/Cntr=0.3,0.1

Type RM Length L Ch R = 1 ,3377.232,127.475200,127.475200,127.475200
XS GIS Cut Line= 6
1250084.57596585837578.2370759251250020.39640325837626.277316913
1249970.91723657837665.3398169131249927.79049379837716.880404085
1249895.39640325837762.9960668981249866.75056991837795.548150241
#Sta/Elev= 30
9884.718150.36259893.972143.74819914.457130.55329922.651124.60489965.80795.72956
9976.13689.809889980.31688.089299981.69187.842079986.98688.059299992.85686.51319
10001.2285.7595410009.5886.4821610018.7585.9147510033.3586.1216410059.02 85.6273
10067.5785.7245710071.8586.1494910077.0687.6155210082.1788.3124110088.9688.79346
10101.3888.6579910105.3988.9764310114.9191.8284710121.4292.7693610145.4899.45071
10153.68 102.75210159.39105.976410171.16114.0334 10179.9121.290610194.85131.1174
#Mann= 3 , 0 , 0
9884.718    0.12       09884.718    0.12       010194.85    0.12       0
#XS Ineff= 2 , 0
       0                10081.03       0
Bank Sta=9884.718,10194.85
Exp/Cntr=0.3,0.1

Type RM Length L Ch R = 1 ,3249.757,136.219800,136.219800,136.219800
XS GIS Cut Line= 6
1250015.53636387837463.7033440771249976.43622276837492.342126757
1249930.92759743837532.1834322511249806.59525815837653.223563433
1249752.04832989837697.4916003791249668.87304711837757.742342353
#Sta/Elev= 30
9845.502137.10649860.641   130.79870.756125.72989882.957120.97349893.968113.3336
 9918.86100.34559948.74482.300799956.39779.382089963.09977.514789972.42776.44001
9995.74675.6929710009.5576.7799510023.4275.9409510035.2976.5098210051.1478.17735
10065.01  80.31910103.5883.2902210147.1388.0122710172.4891.6946610189.3892.07156
10198.2694.0236910210.0199.6297610214.06101.042210226.21101.820510246.47101.1927
 10262.4104.413410274.82108.107910278.88108.800510286.98108.470410300.97112.3883
#Mann= 3 , 0 , 0
9845.502    0.12       09845.502    0.12       010300.97    0.12       0
#XS Ineff= 2 , 0
       09938.435        10074.45       0
Bank Sta=9845.502,10300.97
Exp/Cntr=0.3,0.1

Type RM Length L Ch R = 1 ,3113.537,133.840400,133.840400,133.840400
XS GIS Cut Line= 6
1250012.58390322837427.0585668981249894.09431988837441.381483585
 1249838.5334655837452.5041026771249804.98412728837464.709884271
1249789.27030155837472.4715214671249657.53669715837560.172830611
#Sta/Elev= 30
9802.192132.57819813.132127.32459816.436 125.388 9832.96114.07949842.874106.3336
9849.483101.81219866.00793.492249885.83582.495669899.05476.354739902.35975.56542
9935.57975.486779945.61775.887359965.69274.803369972.38473.84943 9975.7372.91012
9993.06766.663169996.55566.3230510003.5267.0156510017.6967.1330110028.6766.75539
10036.3465.9056210040.2866.4826210071.8175.0921110085.0479.3480710096.8882.51571
 10102.8 85.316310115.1790.37005 10132.498.4318210170.35120.299710189.69126.4928
#Mann= 3 , 0 , 0
9802.192    0.12       09802.192    0.12       010189.69    0.12       0
#XS Ineff= 2 , 0
       09942.081        10087.41       0
Bank Sta=9802.192,10189.69
Exp/Cntr=0.3,0.1

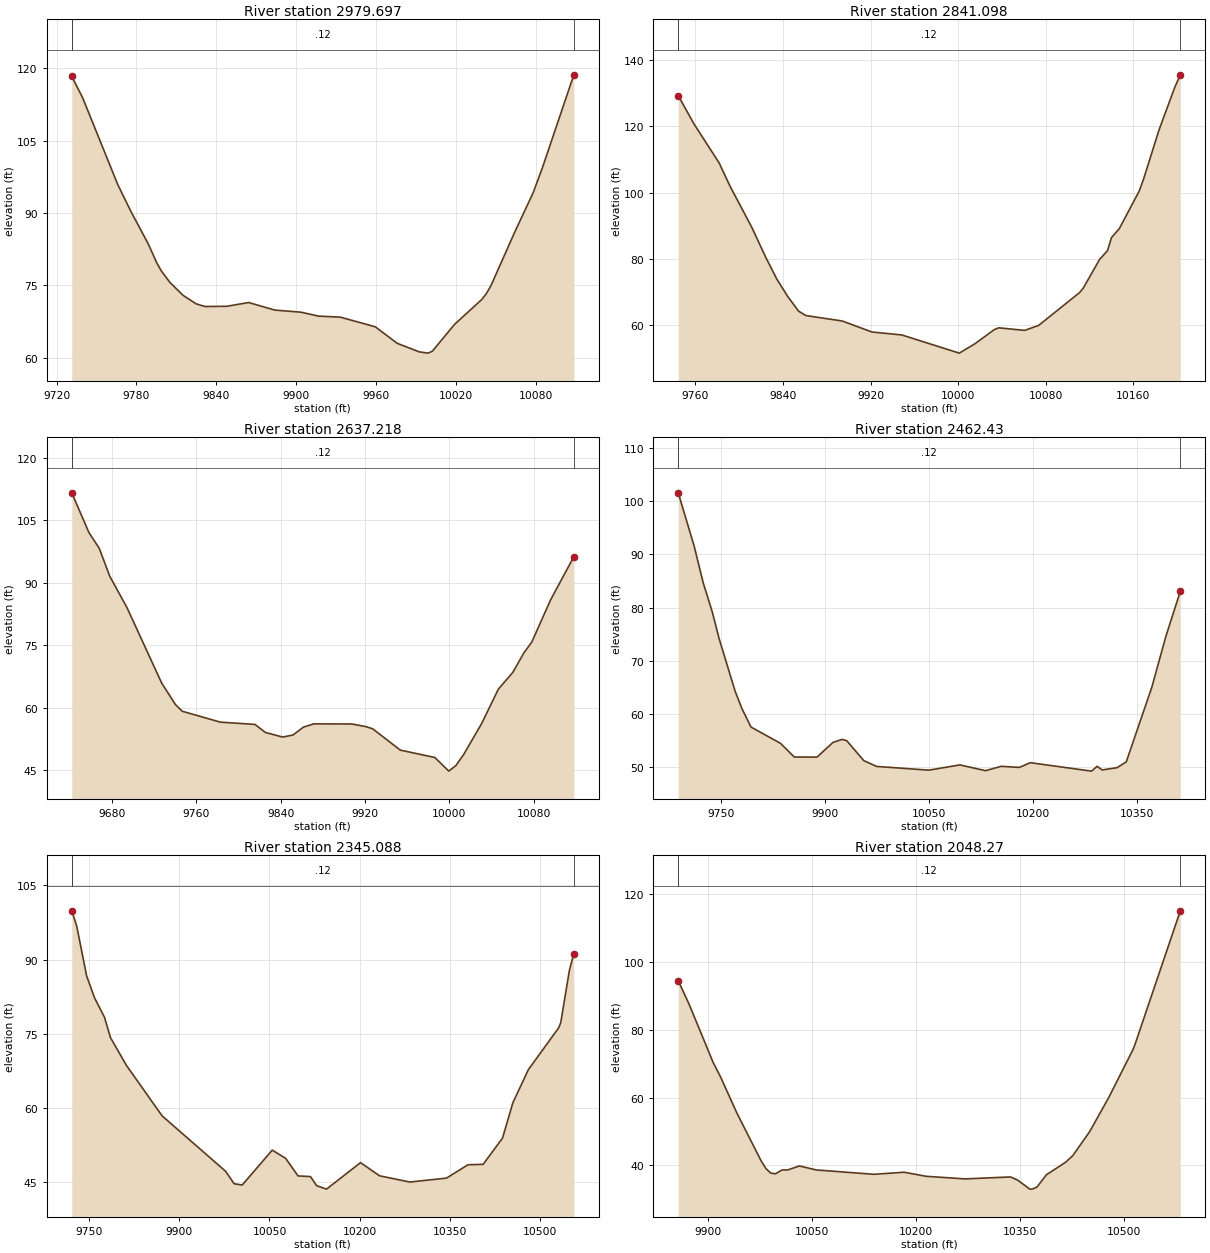
Type RM Length L Ch R = 1 ,2979.697,138.599100,138.599100,138.599100
XS GIS Cut Line= 6
1250016.49015325837355.4439835851249795.28925702837353.984657302
  1249755.442628837356.8298849461249732.46976843 837360.53099151
1249708.89715344837366.7158943561249645.09326556837391.345905155
#Sta/Elev= 30
9731.375118.3127 9739.58 113.8549765.82795.96464 9775.6790.402379788.79483.62659
9795.35579.616679798.63678.021419805.19875.605579815.04172.947579824.88471.18524
9831.44670.64284 9847.8570.688699864.25571.46885 9883.9469.902889903.62669.46498
9916.74968.655239933.15368.438659959.40966.43918 9975.8663.023069992.31161.25931
9998.95660.9885710002.2861.3846710018.9666.9497110039.3172.07523 10042.873.29955
10046.31  74.977 10063.985.8982510077.9694.18323   1008599.4249310108.56 118.625
#Mann= 3 , 0 , 0
9731.375    0.12       09731.375    0.12       010108.56    0.12       0
#XS Ineff= 2 , 0
       09914.717                       0
Bank Sta=9731.375,10108.56
Exp/Cntr=0.3,0.1

Type RM Length L Ch R = 1 ,2841.098,203.879700,203.879700,203.879700
XS GIS Cut Line= 6
1250015.97944719837188.4026062491249877.09055832 837200.55538404
1249801.56972498837221.3887173681249772.05583611 837237.88177292
1249725.45821339837299.3313924071249609.95027411837355.482838854
#Sta/Elev= 30
9744.461129.24549758.771120.72069781.825108.93399791.705101.94619811.46589.60637
9824.63980.287949834.51973.863369844.39968.685429854.27964.255899860.86662.91931
9894.13161.274489921.35857.948569948.58557.0615510001.0651.5812310015.2754.38989
10032.9858.6618710037.1259.21785 10060.758.4318910073.4659.9267610110.9569.85409
10114.2771.2079510129.1379.8223910136.3582.4621210139.9686.3890110147.1889.13718
10165.24100.385710169.18103.9365 10183.3118.780610197.74131.694310202.84 135.498
#Mann= 3 , 0 , 0
9744.461    0.12       09744.461    0.12       010202.84    0.12       0
#XS Ineff= 2 , 0
       09951.294                       0
Bank Sta=9744.461,10202.84
Exp/Cntr=0.3,0.1

Type RM Length L Ch R = 1 ,2637.218,174.788500,174.788500,174.788500
XS GIS Cut Line= 6
1249998.32898426  837108.61383311249706.74042159837106.420386434
1249642.26019216837109.5293141451249631.49457157837112.583357409
1249592.94703981 837130.315222011249532.18315092837157.224944219
#Sta/Elev= 30
9641.773111.62139658.063 102.0689667.90698.256839677.74991.609389694.15484.02732
9726.96365.949339740.08760.736819746.64859.117879782.73956.506669815.54855.95877
9825.391 54.03259841.79552.926429851.63853.409059861.48155.306869871.32456.09158
9907.41456.062919920.53855.435919927.099 54.92739953.36949.789359986.21648.00285
9999.40944.7342410006.0946.0713510013.2848.6345810030.6956.2399710046.3964.42794
10060.1768.4841410070.5373.1265110078.1175.7545310096.0685.94558   1011896.27853
#Mann= 3 , 0 , 0
9641.773    0.12       09641.773    0.12       0   10118    0.12       0
#XS Ineff= 2 , 0
       09892.624                       0
Bank Sta=9641.773,10118
Exp/Cntr=0.3,0.1

Type RM Length L Ch R = 1 , 2462.43,117.341400,117.341400,117.341400
XS GIS Cut Line= 6
1250004.88280371837067.0339719951249749.15363702837069.638138667
1249698.11197034836940.9532428381249646.02863702836915.471471995
1249531.44530368836995.1589719951249502.06031576837109.197103798
#Sta/Elev= 30
9688.092101.59439710.94491.622499724.07284.67553  9737.279.175589747.04674.15753
9770.02164.306459779.867 61.01599792.99557.535229835.66154.458659855.35351.89846
9888.17451.883069911.14854.644389924.32855.213239930.96254.969659955.61951.21259
9974.17650.1236710049.4149.4250810094.09 50.411110131.0949.3297110153.6350.14519
10179.9249.9459310195.6450.8308910283.9349.2423510291.9850.1463110299.18 49.4632
10320.6349.8865910333.9550.9835910370.8365.0339610390.9774.5596710411.86 83.0783
#Mann= 3 , 0 , 0
9688.092    0.12       09688.092    0.12       010411.86    0.12       0
#XS Ineff= 2 , 0
       0 9937.85        10144.75       0
Bank Sta=9688.092,10411.86
Exp/Cntr=0.3,0.1

Type RM Length L Ch R = 1 ,2345.088,296.818200,296.818200,296.818200
XS GIS Cut Line= 6
1250095.11717867836981.0096664331249779.14495649836935.002721985
 1249735.7421787836883.7874442241249715.65396877836877.760981252
1249636.78384536836888.1277219851249319.07551204837027.884666433
#Sta/Elev= 30
9721.384 99.86119729.532 96.83579746.04986.709519759.26382.249159775.78178.32809
9785.69274.22601 9812.1268.616839871.58458.379849977.14647.16796 9991.24 44.6553
10004.6344.3818410054.6151.4510410076.9649.7865310097.4546.23523 10118.146.10099
10128.3844.2638910144.84 43.562210201.3248.9247110233.0946.2513710283.2744.99791
 10344.245.7886710380.0548.4935310405.1448.5766210437.3953.8850710454.6161.05099
10480.4167.7480710530.5876.1690610534.17 77.234910548.5187.7898210555.9391.22323
#Mann= 3 , 0 , 0
9721.384    0.12       09721.384    0.12       010555.93    0.12       0
#XS Ineff= 2 , 0
       09953.626        10174.97       0
Bank Sta=9721.384,10555.93
Exp/Cntr=0.3,0.1

Type RM Length L Ch R = 1 , 2048.27,211.885600,211.885600,211.885600
XS GIS Cut Line= 4
 1249882.0614354 836637.611945571249698.23928517 836699.19398357
1249504.45726877836774.3306955551249198.46768543836876.327223346
#Sta/Elev= 30
9857.70594.557569873.368 87.59539907.96870.439219918.34866.289679942.56955.34884
9977.16941.372999984.08939.085759991.00937.728399997.92937.5127710007.6738.64787
10015.2338.6200410032.53  39.82310056.8438.6486910140.0537.3575210183.5237.97489
10215.1936.7727910271.2836.0045610336.9936.5825110347.3635.6479110364.6533.01164
10368.1132.9832110375.03 33.564410388.8637.2328410416.5340.92049 10426.942.89263
10451.1149.9318610478.7860.0597510513.3674.0571910516.8275.8405810581.95115.1705
#Mann= 3 , 0 , 0
9857.705    0.12       09857.705    0.12       010581.95    0.12       0
#XS Ineff= 2 , 0
       0                10136.21       0
Bank Sta=9857.705,10581.95
Exp/Cntr=0.3,0.1

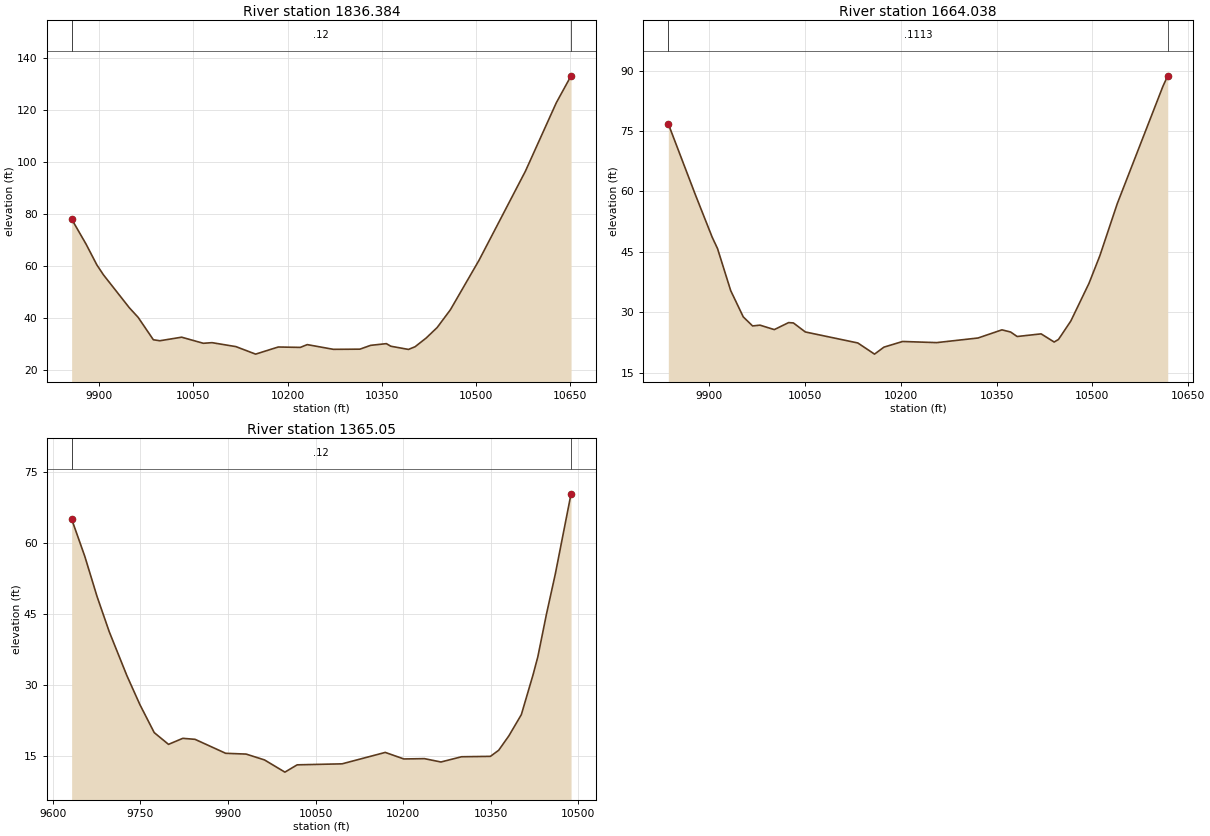
Type RM Length L Ch R = 1 ,1836.384,172.346200,172.346200,172.346200
XS GIS Cut Line= 5
1249849.50935209836429.2786122411249594.86788556836514.308541626
1249572.00125712 836524.810282991249570.17363405836525.622559905
1249103.87544957 836704.17922461
#Sta/Elev= 30
 9856.3178.026919879.15668.46709 9896.4560.447149906.82756.662499948.33443.92985
 9962.1740.300219986.38231.694599996.75931.3124810031.3532.6800110065.9430.34141
10079.77 30.580910117.8229.0599810149.16 26.178610185.1828.9129510220.3128.76149
10231.3329.8320610273.0128.0167810315.1728.0846410332.2529.5511210357.3330.20408
10364.3529.2127510392.4627.98222   1040329.0228510420.5632.3477310438.1336.39425
10459.2143.2228610504.8862.2735210578.6596.4451210627.84122.732110651.25133.0333
#Mann= 3 , 0 , 0
 9856.31    0.12       0 9856.31    0.12       010651.25    0.12       0
#XS Ineff= 2 , 0
       0                10175.54       0
Bank Sta=9856.31,10651.25
Exp/Cntr=0.3,0.1

Type RM Length L Ch R = 1 ,1664.038,298.987800,298.987800,298.987800
XS GIS Cut Line= 5
1249793.08574101836238.306390002 1249501.8216134836396.880109385
1249499.96466002836397.6228907561249441.74196729836426.286169574
1249072.59962988836529.105001122
#Sta/Elev= 30
9836.24176.763249878.85259.093189905.00148.633729913.28345.846259933.86835.43329
9953.564 28.90679968.17426.662619979.71226.8583510002.1325.7553510024.5427.49191
10032.0127.4074910050.6925.1711710132.8522.4415610159.02 19.674610173.7621.40906
10203.0222.8111810256.2822.5287810320.9923.6725510358.4625.6941410372.0825.15263
 10382.324.0410210419.7624.6983610440.1922.67419   1044723.3242310466.26 27.8828
10494.6837.2224310511.7144.0759910538.9656.9876610610.4886.1069410617.9688.67956
#Mann= 3 , 0 , 0
9836.241  0.1113       09836.241  0.1113       010617.96  0.1113       0
#XS Ineff= 2 , 0
       0                10177.27       0
Bank Sta=9836.241,10617.96
Exp/Cntr=0.3,0.1

Type RM Length L Ch R = 1 , 1365.05,186.864600,186.864600,186.864600
XS GIS Cut Line= 4
1249780.06490767 836032.143195571249324.33574098836201.414028898
1249029.60367808836319.3068540541248984.26359075836345.461344689
#Sta/Elev= 30
9632.05665.020119654.58957.162079675.588 48.68599696.58741.204479726.91531.90867
9749.08525.827549773.58319.926389798.08217.441059822.58118.71673 9843.5818.50108
9896.07815.552749931.07615.389849962.574 14.15519997.57311.5772810018.5713.11665
10095.5713.3274610169.5515.7415710201.3614.3608710236.6914.4235110264.9613.71747
 10300.314.8226210349.7714.90827 10363.916.1887110381.5719.2733110402.77 23.7195
10422.7432.0900910431.0435.9373210445.7544.9029110461.0153.4309210487.9970.35645
#Mann= 3 , 0 , 0
9632.056    0.12       09632.056    0.12       010487.99    0.12       0
#XS Ineff= 2 , 0
       0                10090.92       0
Bank Sta=9632.056,10487.99
Exp/Cntr=0.3,0.1