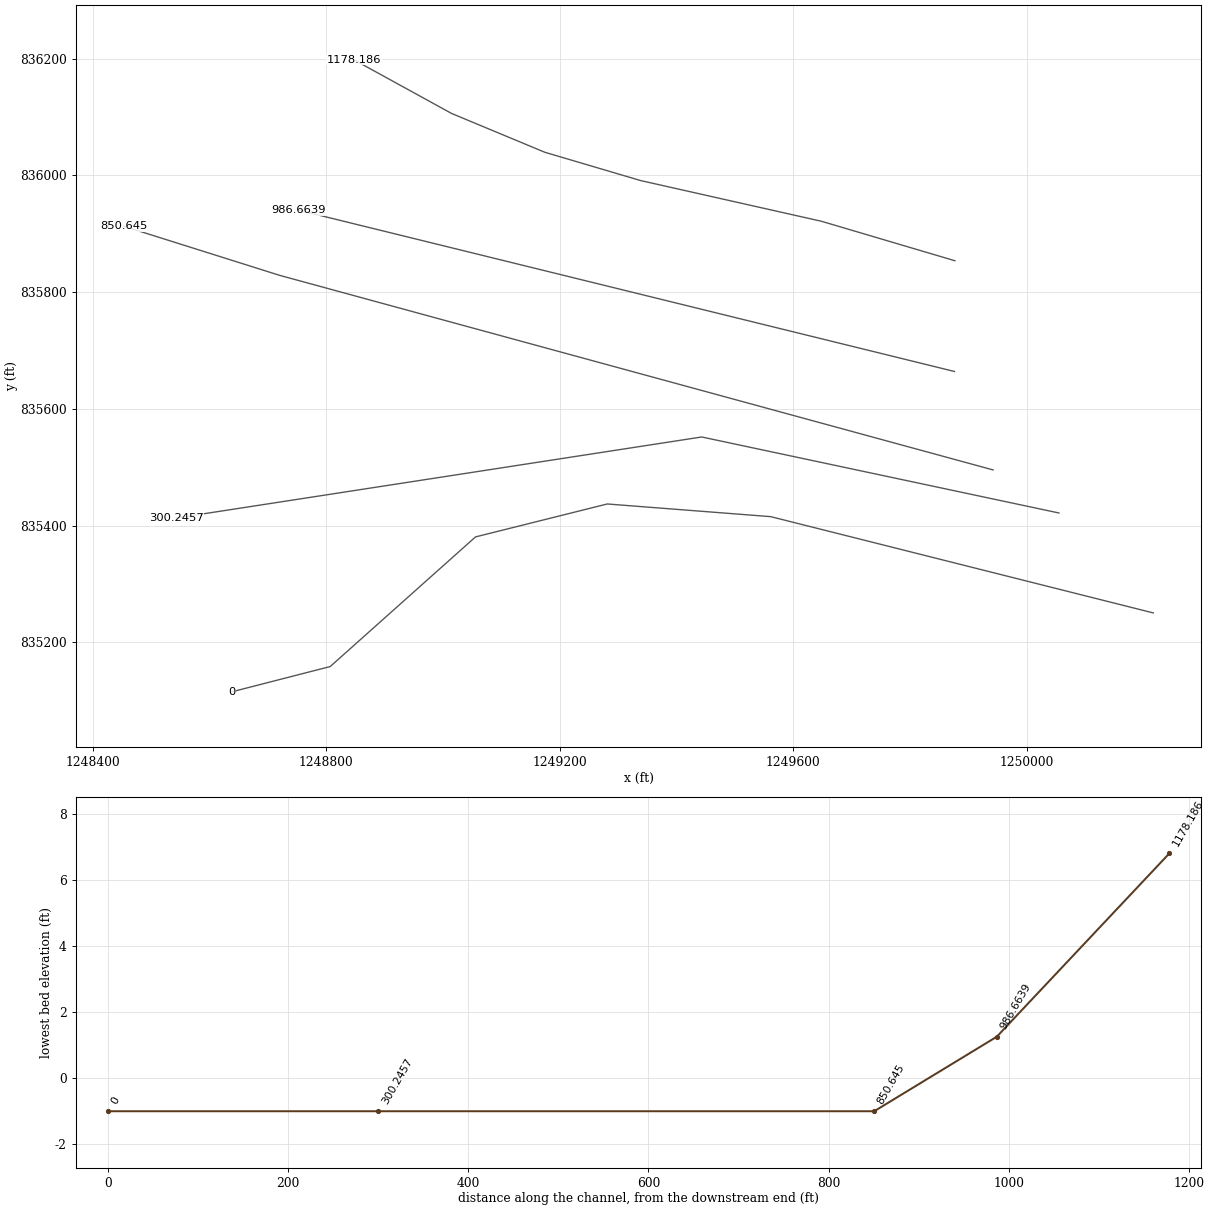
HEC-RAS study 77_ras.prj: 77

--- 77_ras.g01 (geometry) --- (continued)

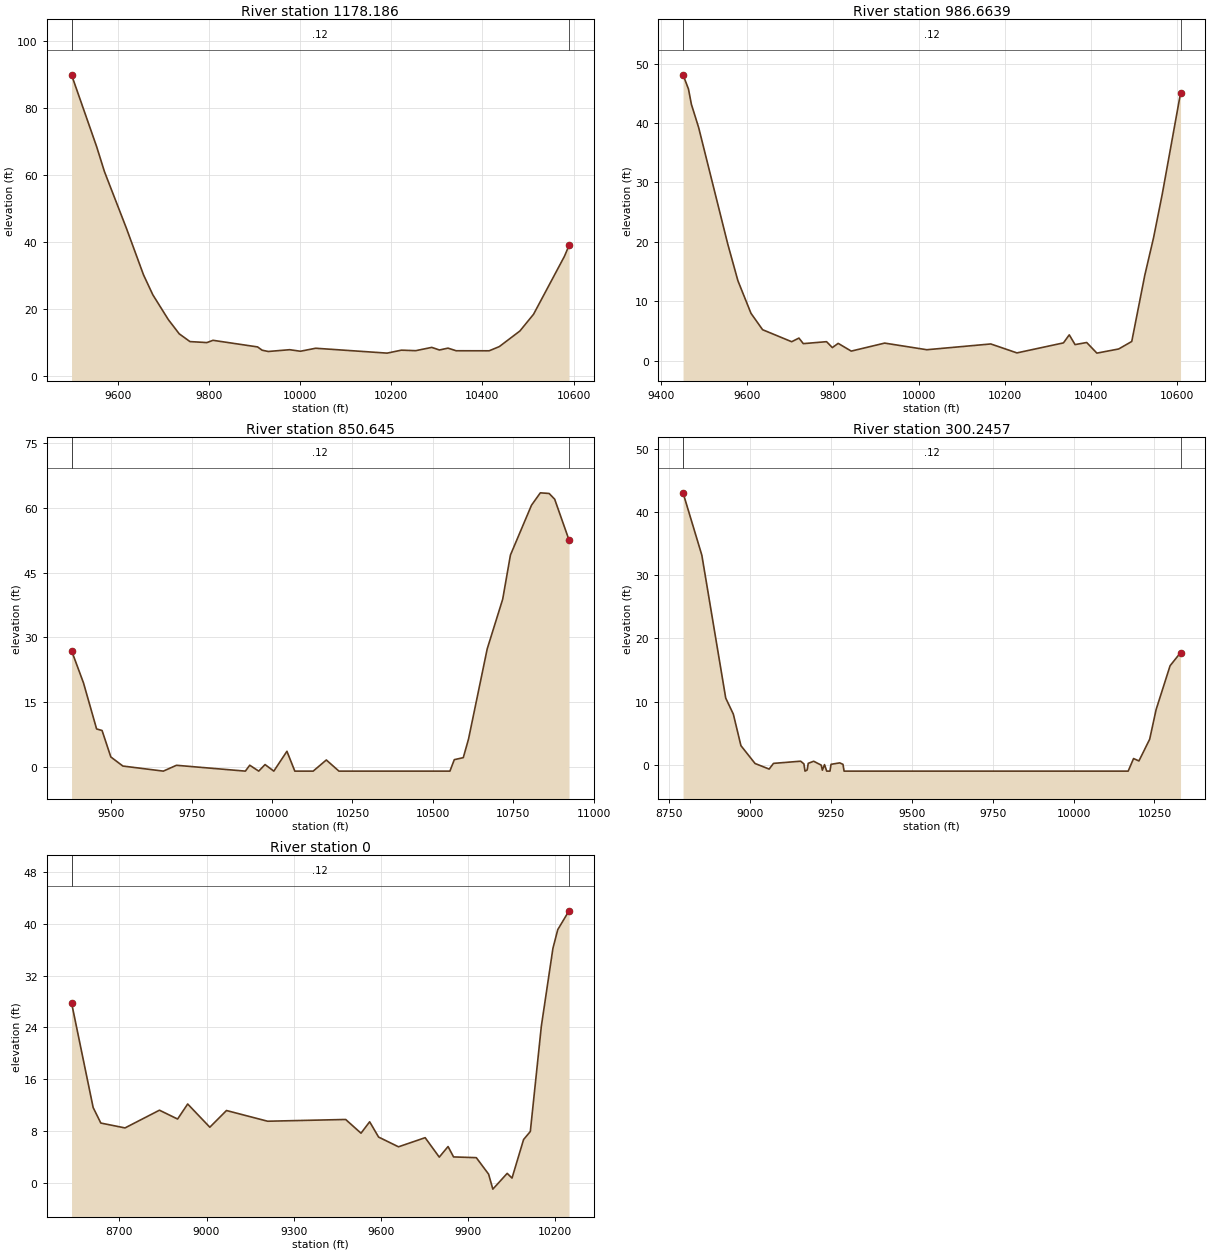
Type RM Length L Ch R = 1 ,1178.186,191.521800,191.521800,191.521800
XS GIS Cut Line= 6
1249877.08125225835853.6861398671249648.28204057835921.350915208
1249338.75760108835991.0110736041249174.48592696836039.549112797
1249014.81850368836105.9966609931248847.54484072836197.891900241
#Sta/Elev= 30
9499.01989.886369554.06368.447289571.25560.970639619.39144.063279656.88530.16527
9677.30724.214389711.34316.799059735.16812.561549758.80410.237389795.9149.944935
9809.40810.619269907.048 8.646349917.1117.6633869930.5297.2854659977.4927.816438
10000.977.35727310034.558.25173210191.246.79443410222.357.67776310253.937.529633
 10289.18.50647810305.967.72933510324.718.28633610342.637.50256110414.977.490877
10437.158.73718910482.3513.39708 10512.3 18.393510580.24 35.741410590.1438.94666
#Mann= 3 , 0 , 0
9499.019    0.12       09499.019    0.12       010590.14    0.12       0
#XS Ineff= 2 , 0
       0 9879.51        10225.08       0
Bank Sta=9499.019,10590.14
Exp/Cntr=0.3,0.1

Type RM Length L Ch R = 1 ,986.6639,136.018900,136.018900,136.018900
XS GIS Cut Line= 2
1249876.19067407835664.0377335851248753.15074003835940.266633421
#Sta/Elev= 30
9451.97748.121379464.60545.726049471.36243.155349488.25539.242569555.827 19.6423
9579.47813.454989609.8857.9609329636.9145.1964449704.4873.173101 9721.383.789677
9731.5162.8502639785.5733.1813729799.0882.1856599812.6022.895594 9843.011.594141
9920.7182.941394 10018.71.82455610167.362.79757610228.17 1.2908610336.292.976564
 10349.84.33160910363.322.68895710390.353.042045   104141.25300310464.681.952073
10495.083.21747610525.4914.4039310545.7620.6808810566.0328.0499910608.4945.03462
#Mann= 3 , 0 , 0
9451.977    0.12       09451.977    0.12       010608.49    0.12       0
#XS Ineff= 2 , 0
       09814.131                       0
Bank Sta=9451.977,10608.49
Exp/Cntr=0.3,0.1

Type RM Length L Ch R = 1 , 850.645,550.399300,550.399300,550.399300
XS GIS Cut Line= 3
1249942.38685122835495.3881611821248720.39655748835828.658241287
1248453.32469004835912.762782976
#Sta/Elev= 30
 9376.7326.933569413.84519.463929454.6538.7758419471.6568.4137959498.8622.287723
9536.2690.1804029662.093  -0.9999702.901 0.354289917.143  -0.9999930.7450.370752
9958.667  -0.9999978.3550.52277810005.56  -0.99910046.373.60226110070.89  -0.999
10127.98  -0.99910168.791.58608810208.05  -0.99910553.07  -0.99910566.671.655825
10594.592.12469610610.886.42790810668.9827.3339410717.1338.8561710741.2149.09153
10806.57 60.620510834.0863.50953 10861.663.35906 10878.862.0221510923.3552.57639
#Mann= 3 , 0 , 0
 9376.73    0.12       0 9376.73    0.12       010923.35    0.12       0
#XS Ineff= 2 , 0
       0 9827.55                       0
Bank Sta=9376.73,10923.35
Exp/Cntr=0.3,0.1

Type RM Length L Ch R = 1 ,300.2457,300.245700,300.245700,300.245700
XS GIS Cut Line= 3
 1250055.2340734835421.6034389591249443.25490671835551.811772302
1248542.64726785835412.922883421
#Sta/Elev= 30
8793.68743.006868851.74933.143388925.54310.546278949.0238.0157428972.503 3.02979
9016.1090.2065399059.714 -0.67329073.1310.2252119156.9880.5707789167.0510.149704
9170.405  -0.9999177.114-0.824739180.4680.2332429197.2390.5643439220.719-0.05827
9224.074   -0.859230.7820.0294769237.491  -0.9999247.554  -0.9999250.9080.078992
9277.7420.3056679287.8050.0720019291.159  -0.99910168.86  -0.99910185.46 0.99133
10202.06 0.6113210235.26  4.046310255.178.73615210298.3315.6638410330.6217.73943
#Mann= 3 , 0 , 0
8793.687    0.12       08793.687    0.12       010330.62    0.12       0
#XS Ineff= 2 , 0
       09348.329                       0
Bank Sta=8793.687,10330.62
Exp/Cntr=0.3,0.1

Type RM Length L Ch R = 1 ,       0,0.000000,0.000000,0.000000
XS GIS Cut Line= 6
1250216.80409998835250.4222821891249561.42215553835415.352837726
1249281.47423887835437.0542266371249055.77979445835380.630615517
1248806.89190325835158.5673848241248637.90034261835115.148984477
#Sta/Elev= 30
8535.49627.800098609.88811.611758636.2739.213143 8719.518.4612948838.04411.19966
8900.4979.8348578935.19312.160279011.3968.569313 9068.7111.151449210.3089.496074
 9478.879.7672869531.672 7.645369561.4449.4117849592.161 7.048089660.692 5.54184
9752.4216.9524269800.9863.948301 9831.255.5839559850.1653.9793259928.4943.863424
9970.7951.3130319985.374  -0.99910034.751.43601310051.35 0.7065610091.196.670049
10114.347.90718410152.3424.2103210192.1536.2209210208.7439.1095910247.5442.01707
#Mann= 3 , 0 , 0
8535.496    0.12       08535.496    0.12       010247.54    0.12       0
#XS Ineff= 2 , 0
       0                               0
Bank Sta=8535.496,10247.54
Exp/Cntr=0.3,0.1